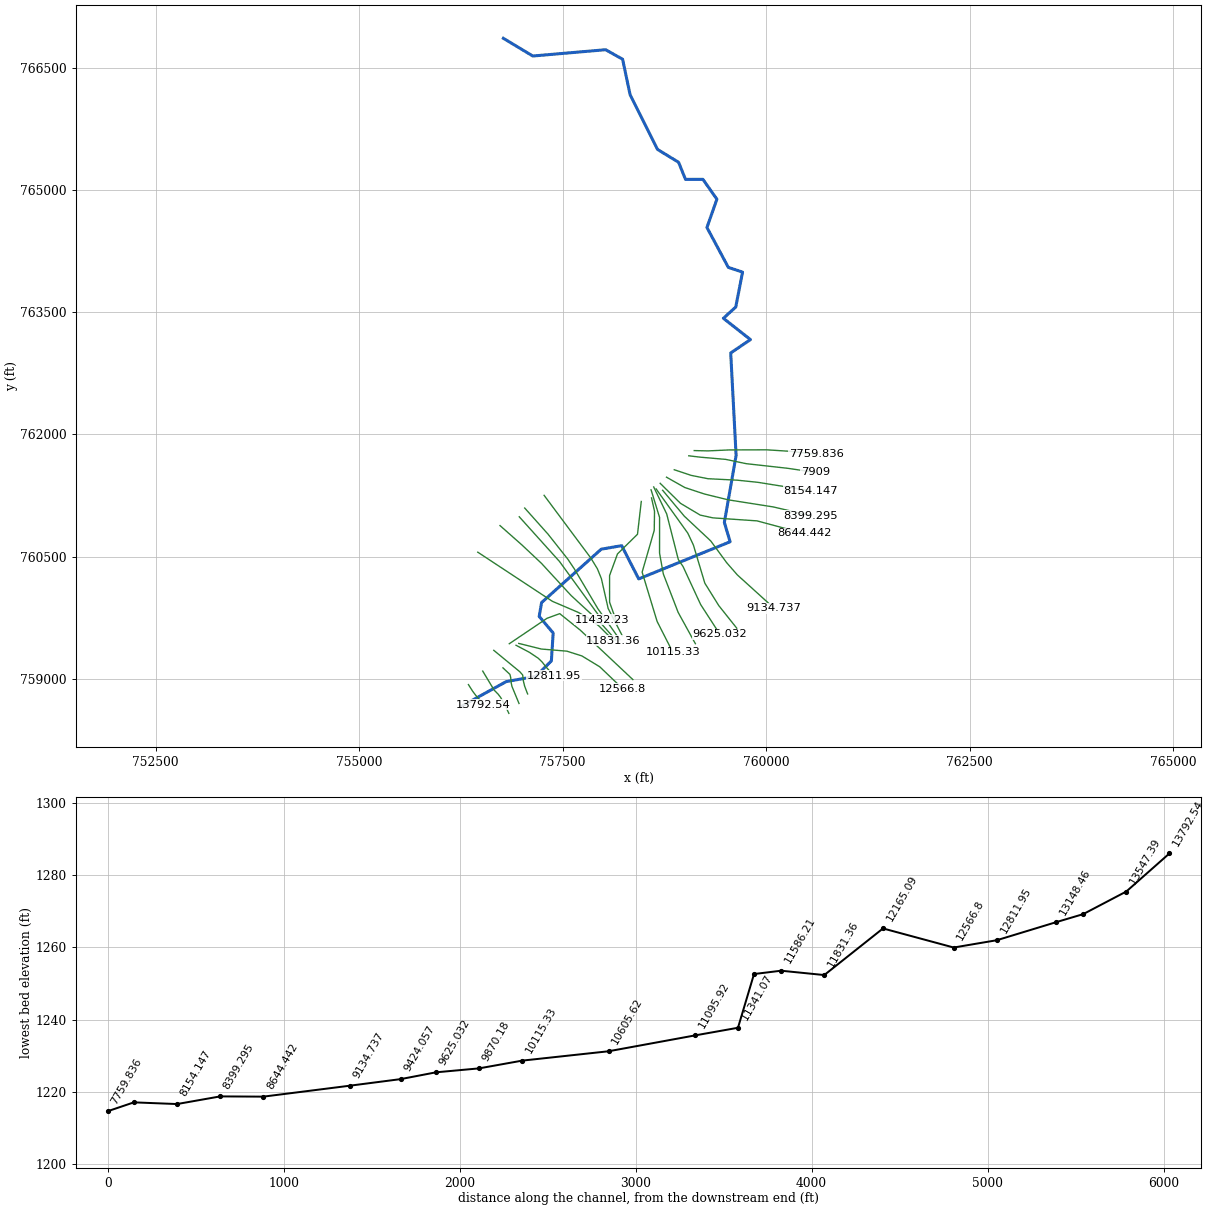
--- 14287_ras.prj (project) ---

Proj Title=14287
Current Plan=p01
Default Exp/Contr=0.3,0.1
English Units
Geom File=g01
Flow File=f01
Plan File=p01
Y Axis Title=Elevation
X Axis Title(PF)=Main Channel Distance
X Axis Title(XS)=Station
BEGIN DESCRIPTION:
RFD model 14287 exported to HEC-RAS
END DESCRIPTION:

--- 14287_ras.p01 (plan) ---

Plan Title=Plan 01
Program Version=4.10
Short Identifier=Plan 01
Geom File=g01
Flow File=f01
Subcritical Flow
Calc Critical at every XS
Secant Critical Depth

--- 14287_ras.f01 (steady flow) ---

Flow Title=Flow 01
Program Version=5.01
Number of Profiles= 6
Profile Names=10yr,25yr,50yr,100yr,100plus,500yr
River Rch & RM=14287,43,13792.54
  345.35  581.07  811.14 1033.38 1508.73 2491.15
River Rch & RM=14287,43,13547.39
  348.76  587.21  820.05 1045.13 1525.89 2517.58
River Rch & RM=14287,43,13302.25
  479.34  815.61 1147.23 1471.03 2147.71 3421.51
River Rch & RM=14287,43,13148.46
  481.28  819.07 1152.24 1477.63 2157.33 3435.53
River Rch & RM=14287,43,12811.95
  486.82  828.98 1166.63 1496.58 2185.01  3475.9
River Rch & RM=14287,43, 12566.8
   492.8  839.66 1182.13 1516.97 2214.78 3519.17
River Rch & RM=14287,43,12165.09
  501.98  856.14 1206.12 1548.66 2261.04 3586.75
River Rch & RM=14287,43,11831.36
  449.31   794.2  1145.2 1502.41 2193.52 3667.49
River Rch & RM=14287,43,11586.21
  945.98 1648.69 2357.04 3064.45 4474.09 6622.85
River Rch & RM=14287,43,11432.23
   946.7 1649.98 2358.93 3066.94 4477.73 6627.66
River Rch & RM=14287,43,11341.07
  959.85 1673.66 2393.53 3112.74  4544.6  6716.4
River Rch & RM=14287,43,11095.92
  965.25 1683.34 2407.64 3131.37  4571.8 6752.24
River Rch & RM=14287,43,10605.62
  998.17 1742.67 2494.36 3246.22 4739.48 6974.01
River Rch & RM=14287,43,10115.33
 1271.28 2215.02 3166.95 4115.79 6009.05 8521.51
River Rch & RM=14287,43, 9870.18
 1278.79 2228.56 3186.77 4142.06 6047.41 8570.47
River Rch & RM=14287,43,9625.032
 1287.49 2244.16  3209.5 4172.06 6091.21 8625.83
River Rch & RM=14287,43,9424.057
 1297.07 2261.48 3234.88 4205.73 6140.37 8688.62
River Rch & RM=14287,43,9134.737
  1337.5 2333.59 3339.63 4343.61 6341.67 8940.15
River Rch & RM=14287,43,8644.442
 1348.64 2353.65 3368.94  4382.4  6398.3 9011.66
River Rch & RM=14287,43,8399.295
 1349.62 2355.42 3371.53 4385.84 6403.33 9018.05
River Rch & RM=14287,43,8154.147
 1350.43  2356.9  3373.7 4388.71 6407.52 9023.38
River Rch & RM=14287,43,    7909
 1358.91 2372.23 3396.18 4418.56 6451.09 9078.69
River Rch & RM=14287,43,7759.836
 1361.19 2376.36 3402.23 4426.58 6462.81 9093.56
River Rch & RM=14287,43,7418.705
 1371.11 2394.32 3428.56 4461.53 6513.83 9158.24
River Rch & RM=14287,43,7080.266
 1373.21 2398.13 3434.15 4468.95 6524.67 9172.01
River Rch & RM=14287,43,6814.779
 1455.75 2547.81 3653.88 4760.87 6950.87 9710.86
River Rch & RM=14287,43,6687.342
 1456.07 2548.39 3654.72    4762 6952.52 9712.93
River Rch & RM=14287,43,6575.892
 1518.67 2661.65 3820.77 4982.35 7274.2310115.29
River Rch & RM=14287,43, 6250.02
 1520.09 2664.22 3824.55 4987.36 7281.5510124.45
River Rch & RM=14287,43,5835.358
 1523.55  2670.5 3833.77 4999.62 7299.4410146.84
River Rch & RM=14287,43,5341.668
 1531.27 2684.51 3854.33 5026.93 7339.3210196.63
River Rch & RM=14287,43,5094.824
 1532.38 2686.51 3857.26 5030.83 7345.0110203.73
River Rch & RM=14287,43,4847.979
 1541.38 2702.82 3881.19 5062.59 7391.3910261.51
River Rch & RM=14287,43,4601.134
 1542.17 2704.25 3883.29 5065.38 7395.4610266.58
River Rch & RM=14287,43,4354.289
 1548.81 2716.25  3900.9 5088.76  7429.610309.06
River Rch & RM=14287,43,4107.444
 1550.07 2718.54 3904.25 5093.22  7436.110317.15
River Rch & RM=14287,43,3860.599
 1555.11 2727.67 3917.65 5111.01 7462.0710349.46
River Rch & RM=14287,43,3613.755
  1555.9  2729.1 3919.75 5113.79 7466.1310354.51
River Rch & RM=14287,43, 3366.91
 1566.15 2747.65 3946.95  5149.9 7518.8610420.01
River Rch & RM=14287,43, 2873.22
 1566.46 2748.22 3947.79 5151.01 7520.4810422.03
Boundary for River Rch & Prof#=14287,43,1
Up Type= 0
Dn Type= 2
Boundary for River Rch & Prof#=14287,43,2
Up Type= 0
Dn Type= 2
Boundary for River Rch & Prof#=14287,43,2
Up Type= 0
Dn Type= 2
Boundary for River Rch & Prof#=14287,43,2
Up Type= 0
Dn Type= 2
Boundary for River Rch & Prof#=14287,43,2
Up Type= 0
Dn Type= 2
Boundary for River Rch & Prof#=14287,43,2
Up Type= 0
Dn Type= 2

--- 14287_ras.g01 (geometry) ---

Geom Title=14287
Program Version=4.10

River Reach=14287,43
Reach XY= 30
756249.093937159758657.008073792756805.623274326758963.536465719
757167.845496565759027.703132346757360.576736689759217.363333076
757382.523515999 759560.94473961757210.717717111759764.347007245
757240.427127093759934.680957854757973.181144714760590.404521242
758224.431144714 760633.73785457 758433.32003355760225.265632346
759556.614504695760681.647828996759485.810774356760918.839706436
759630.116329879 761741.68692866759563.852441013763001.259845316
759806.352441013763165.426512003759473.852441013763427.093178675
759625.935774297763565.426512003 759709.26910764 763994.59317863
759534.685774297764052.509845316759271.907996535764542.787623093
759394.130218774764890.009845331759222.185774297765134.870956436
759008.559388846765133.886450469758923.490134865765343.955986947
758664.513680041765501.928566948758327.708124489766174.845233634
758235.347013384766610.261900321758027.013680071766726.928566948
757131.995477378766649.514565721 756771.27160123766866.749237612

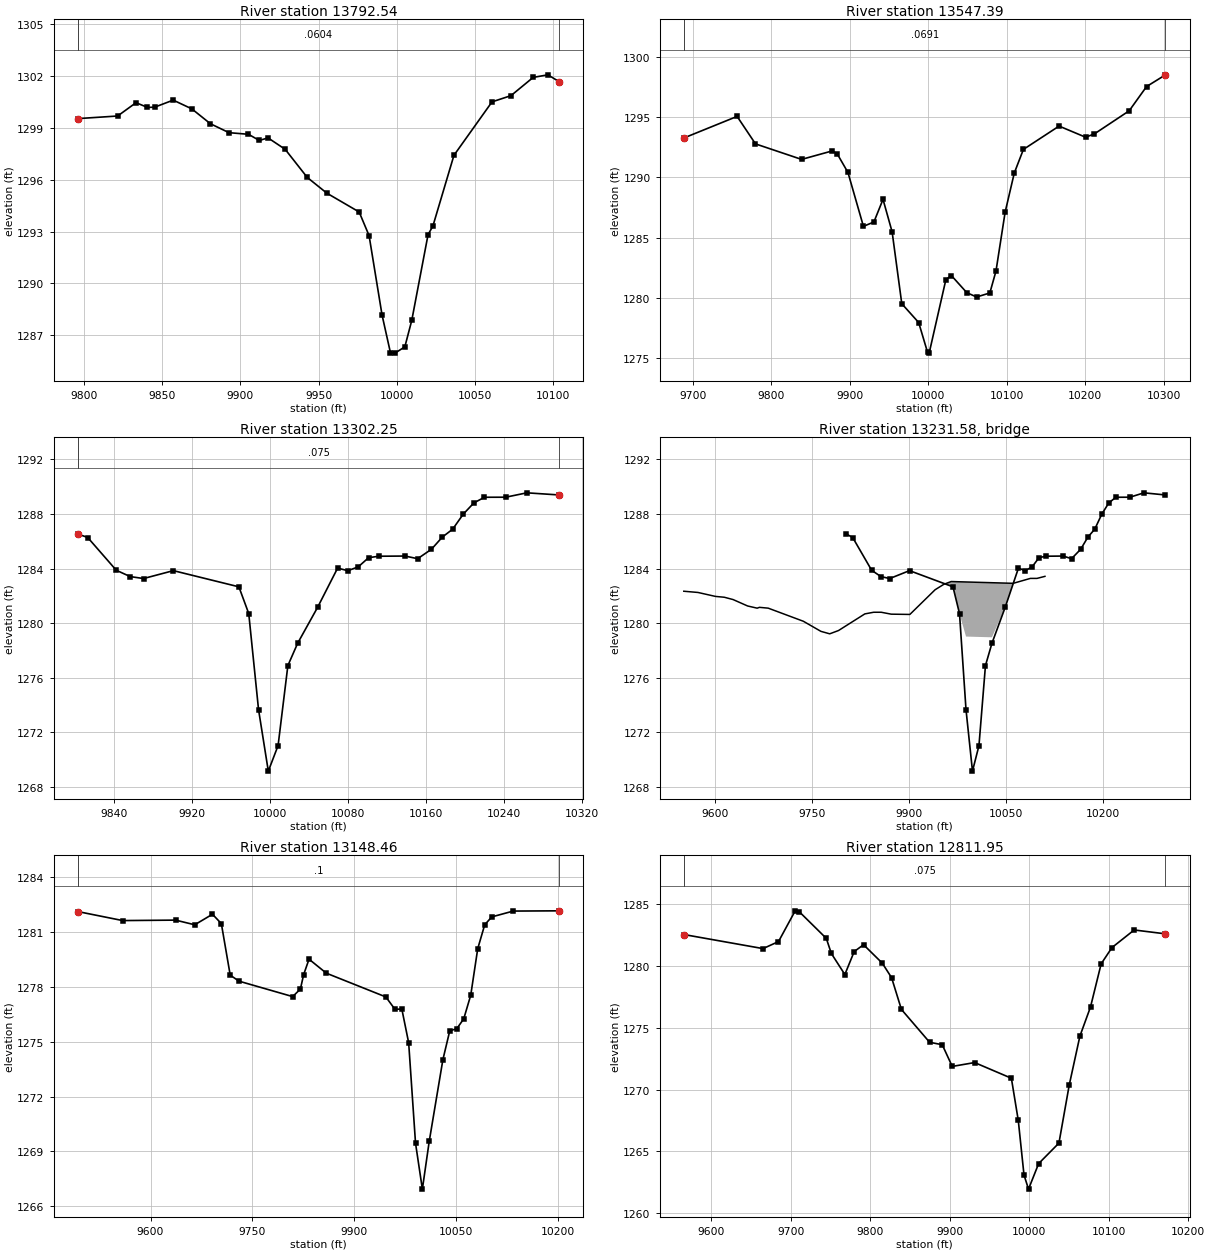
Type RM Length L Ch R = 1 ,13792.54,245.147500,245.147500,245.147500
XS GIS Cut Line= 6
756341.405599806758926.852976562756394.049087534758843.930926487
756433.037268371758792.471382093756486.852353285758734.203519491
756515.100984543758693.127880564756523.069324774758678.602924874
#Sta/Elev= 30
9795.7021299.5369821.3281299.6879833.1051300.4589840.4521300.1849845.0161300.198
9856.9261300.6069868.8361300.1019880.747 1299.249892.6571298.7239905.1351298.629
9912.0641298.2739917.681 1298.429928.6231297.7619942.7731296.1349955.3191295.223
9976.0281294.1339982.3851292.7659990.6881288.1729996.0611285.992    99991285.966
10005.291286.33110009.741287.86810020.171292.82810023.241293.31410036.741297.413
10061.121300.50510073.261300.86510087.491301.92210096.94 1302.0710104.231301.666
#Mann= 3 , 0 , 0
9795.702  0.0604       09795.702  0.0604       010104.23  0.0604       0
#XS Ineff= 2 , 0
       0                               0
Bank Sta=9795.702,10104.23
Exp/Cntr=0.3,0.1

Type RM Length L Ch R = 1 ,13547.39,245.147500,245.147500,245.147500
XS GIS Cut Line= 6
756517.025113535759092.624667069756655.951895228758860.959143029
756709.956360921758805.241383048756738.302335289758766.955031247
756801.623687168758651.176371889756838.380178185 758573.14773918
#Sta/Elev= 30
9688.3581293.273 9756.271295.0669779.7131292.7859838.4371291.4989877.8341292.208
9884.1741291.9219897.5331290.4149917.2321285.9449930.6011286.3059942.2081288.183
9953.8141285.4849966.1241279.5249987.6551277.961    9999 1275.48   100011275.423
10022.311281.52210029.311281.86110048.991280.43910061.441280.08210078.341280.414
10086.161282.23510097.811287.11810109.461290.363 10121.11292.32710166.581294.263
10200.351293.339 10211.61293.616 10255.91295.53110278.011297.54110302.161298.516
#Mann= 3 , 0 , 0
9688.358  0.0691       09688.358  0.0691       010302.16  0.0691       0
#XS Ineff= 2 , 0
       09934.876        10028.77       0
Bank Sta=9688.358,10302.16
Exp/Cntr=0.3,0.1

Type RM Length L Ch R = 1 ,13302.25,153.785300,153.785300,153.785300
XS GIS Cut Line= 6
756765.540447593759132.077676505756851.140713965759052.089629344
756860.407741765759014.787932602756867.813778344758942.258027404
756877.205828629758902.029173971756962.878910814758694.658514965
#Sta/Elev= 30
9802.8931286.5449813.2591286.2759842.5531283.8779856.8991283.4129870.5851283.271
9901.1391283.8499968.3821282.6639978.4941280.7029988.5461273.669 9998.57 1269.16
 10008.61271.03110018.641276.89110028.681278.52910049.15 1281.1610069.691284.036
10080.231283.84410090.871284.12810101.52  1284.810112.171284.90510138.981284.918
10151.821284.72410165.981285.41510177.211286.31210187.741286.88510198.621287.987
 10209.5 1288.8110220.381289.22510242.141289.229 10263.9 1289.55 10297.21289.393
#Mann= 3 , 0 , 0
9802.893   0.075       09802.893   0.075       0 10297.2   0.075       0
#XS Ineff= 2 , 0
       09943.589        10082.12       0
Bank Sta=9802.893,10297.2
Exp/Cntr=0.3,0.1

Type RM Length L Ch R = 3 ,13231.58,,,
BEGIN DESCRIPTION:
END DESCRIPTION:
Bridge Culvert--1,0,-1,-1, 0
Deck Dist Width WeirC Skew NumUp NumDn MinLoCord MaxHiCord MaxSubmerge Is_Ogee
61.892650,30.000000,2.6,0, 27, 27, , , 0.95, 0, 0,0,,
 9551.93 9573.82 9601.00 9614.59 9628.18 9650.65 9665.42 9668.96 9682.55 9736.91
 9764.09 9777.68 9791.27 9832.04 9845.63 9857.39 9872.81 9901.69 9940.76 9954.35
 9965.60 9965.6010061.6010061.6010088.1310098.3510110.68
 1282.34 1282.25 1281.96 1281.90 1281.73 1281.26 1281.10 1281.16 1281.10 1280.14
 1279.40 1279.22 1279.46 1280.68 1280.80 1280.80 1280.66 1280.64 1282.45 1282.85
 1283.05 1283.05 1282.92 1282.92 1283.28 1283.28 1283.43
  282.34  282.25  281.96  281.90  281.73  281.26  281.10  281.16  281.10  280.14
  279.40  279.22  279.46  280.68  280.80  280.80  280.66  280.64  282.45  282.85
  283.05 1279.05 1278.92  282.92  283.28  283.28  283.43
 9551.93 9573.82 9601.00 9614.59 9628.18 9650.65 9665.42 9668.96 9682.55 9736.91
 9764.09 9777.68 9791.27 9832.04 9845.63 9857.39 9872.81 9901.69 9940.76 9954.35
 9966.79 9966.7910062.7910062.7910088.1310098.3510110.68
 1282.34 1282.25 1281.96 1281.90 1281.73 1281.26 1281.10 1281.16 1281.10 1280.14
 1279.40 1279.22 1279.46 1280.68 1280.80 1280.80 1280.66 1280.64 1282.45 1282.85
 1283.05 1283.05 1282.91 1282.91 1283.28 1283.28 1283.43
  282.34  282.25  281.96  281.90  281.73  281.26  281.10  281.16  281.10  280.14
  279.40  279.22  279.46  280.68  280.80  280.80  280.66  280.64  282.45  282.85
  283.05 1279.05 1278.91  282.91  283.28  283.28  283.43
BR Coef=-1 , 0 , 0 ,, 0 ,,,0.8,0,1,0,
WSPro=,,,, 1 ,,,, 0 ,,,, 0 ,,,,-1 ,-1 ,-1 , 0 , 0 , 0 , 0 , 0
BC Design=,, 0 ,, 0 ,,,,,,

Type RM Length L Ch R = 1 ,13148.46,336.509800,336.509800,336.509800
XS GIS Cut Line= 6
756652.952169001759347.649546325756970.974036455759086.188615069
757007.868305832759045.157425761757018.278325975758963.698672935
 757031.93327564758907.929459155757068.411124498 758812.21233812
#Sta/Elev= 30
9492.6591282.1179559.0141281.6229636.8041281.6479665.0291281.3929691.1361281.968
 9704.191281.4569717.2441278.6399730.1521278.309 9809.161277.4659820.5381277.877
9825.356 1278.679833.2511279.5119858.6761278.7469946.3521277.4469959.7471276.767
9969.8281276.7899979.908 1274.949989.9891269.45310000.071266.93710010.151269.547
10030.311274.023 10040.41275.59610050.671275.70710060.961276.24910071.261277.541
10081.551280.08410091.851281.39410102.221281.82310133.861282.14210201.641282.155
#Mann= 3 , 0 , 0
9492.659     0.1       09492.659     0.1       010201.64     0.1       0
#XS Ineff= 2 , 0
       09930.686        10104.59       0
Bank Sta=9492.659,10201.64
Exp/Cntr=0.3,0.1

Type RM Length L Ch R = 1 ,12811.95,245.147500,245.147500,245.147500
XS GIS Cut Line= 6
756926.533931624759409.954846587757090.527173493759323.363342172
757200.216932728759249.831898585757244.529584458759206.995807325
757307.161732941759128.803086751757393.313794762759036.799006328
#Sta/Elev= 30
9565.752 1282.55 9665.351281.4119684.7981281.978 9705.791284.4679710.8051284.401
9744.9251282.2379751.2111281.0199768.2231279.3149779.9781281.1729791.7321281.725
9815.2411280.2379826.9961279.0569839.331 1276.499874.8031273.831 9890.651273.635
9903.2291271.878 9931.36 1272.19 9977.581270.9229986.2621267.507 9993.461263.091
9999.135 1261.9510011.891264.01910037.371265.67510050.341270.379 10063.71274.322
10077.07 1276.6910090.431280.17610104.061281.49510131.981282.91810171.341282.604
#Mann= 3 , 0 , 0
9565.752   0.075       09565.752   0.075       010171.34   0.075       0
#XS Ineff= 2 , 0
       09863.251                       0
Bank Sta=9565.752,10171.34
Exp/Cntr=0.3,0.1

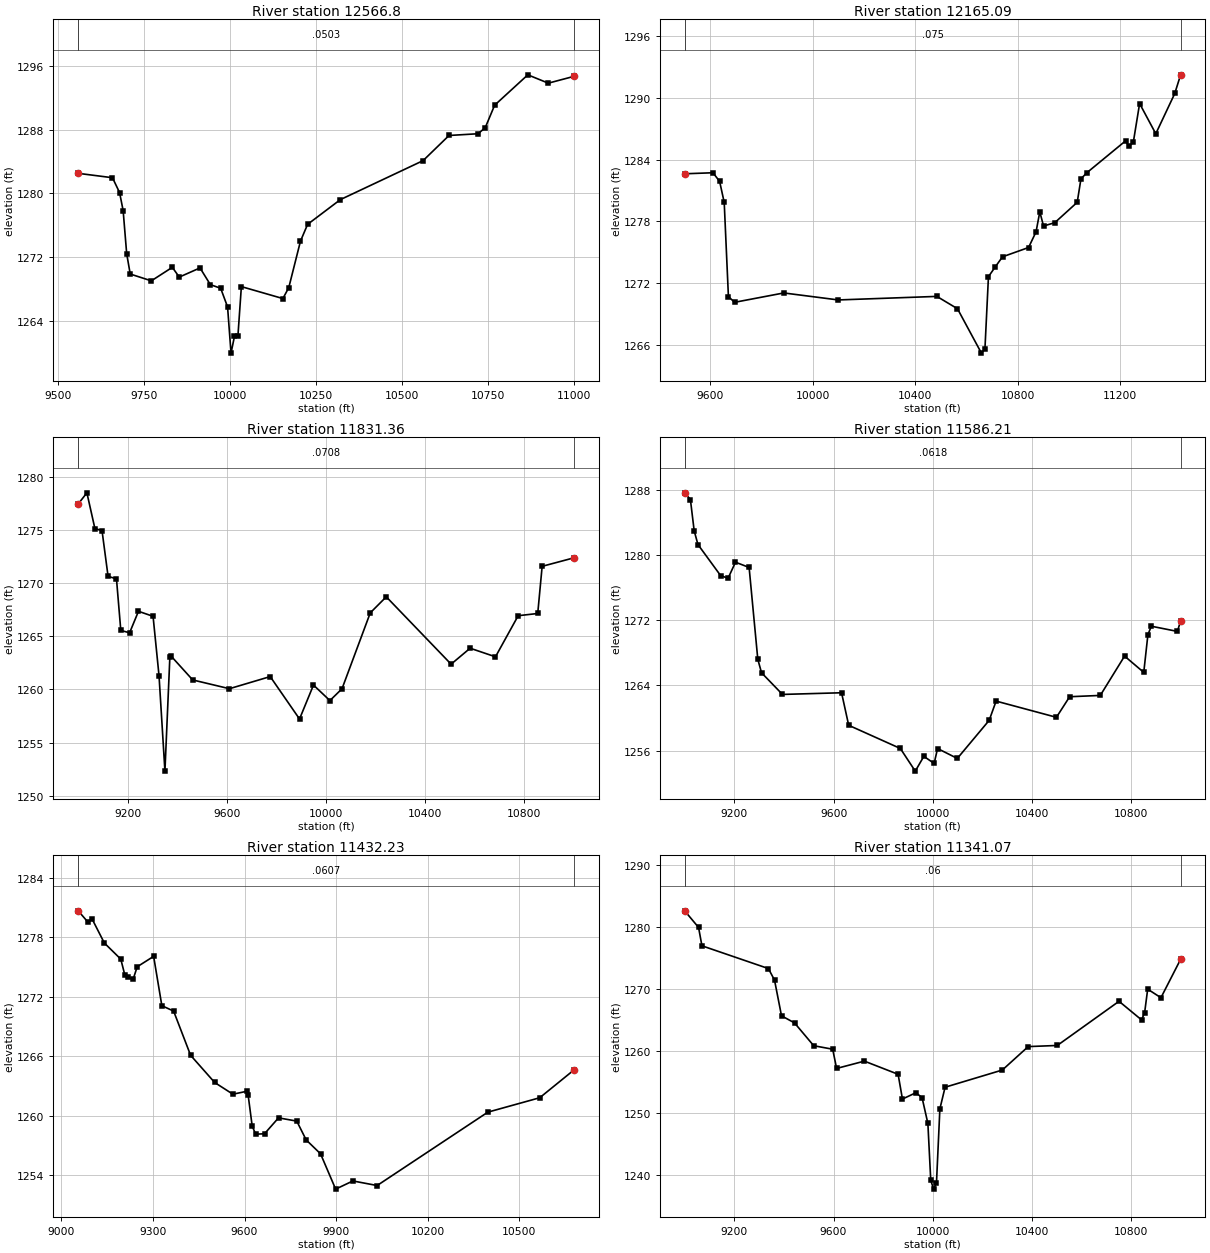
Type RM Length L Ch R = 1 , 12566.8,401.716700,401.716700,401.716700
XS GIS Cut Line= 6
756960.099180127759432.618561391757237.525414176759363.584006521
  757551.1946296759337.373237975757735.862294884759278.717911348
757954.593273407759145.704781304758236.523116172758876.926357058
#Sta/Elev= 30
9558.7881282.5329658.4171281.9819679.1351280.105 9689.431277.8499699.7241272.429
9710.0191269.8719771.4131269.0149832.4231270.7159852.6521269.4859912.9861270.639
9943.0031268.538 9973.02 1268.089993.0791265.73510003.121259.92410013.171262.037
10023.191262.083 10033.21268.28910153.911266.78610171.051268.15910205.061274.004
 10225.81276.117   103211279.22610561.62 1284.1310637.061287.29410721.351287.511
10742.361288.27510769.631291.09710866.16 1294.9210925.751293.87211000.891294.734
#Mann= 3 , 0 , 0
9558.788  0.0503       09558.788  0.0503       011000.89  0.0503       0
#XS Ineff= 2 , 0
       09788.253        10173.22       0
Bank Sta=9558.788,11000.89
Exp/Cntr=0.3,0.1

Type RM Length L Ch R = 1 ,12165.09,333.725900,333.725900,333.725900
XS GIS Cut Line= 5
756843.430105984759428.739621043757306.971772641759741.239621043
757463.221772641  759798.5312877757715.825939327759595.406287685
758361.659272641758988.635454357
#Sta/Elev= 30
9499.9261282.6239610.3611282.7239636.3511281.884 9654.24 1279.849670.6631270.694
9694.7831270.1419886.801 1271.0510099.471270.37110484.311270.71510564.731269.516
10658.171265.20610671.891265.60110685.611272.63110713.051273.611 10740.51274.559
10842.221275.46310871.421276.98710886.031278.92910900.631277.55110944.451277.873
11032.071279.85111046.681282.132 11069.81282.72611220.731285.81811234.461285.275
11251.141285.70111275.621289.44411338.77 1286.5111412.83 1290.4211435.691292.233
#Mann= 3 , 0 , 0
9499.926   0.075       09499.926   0.075       011435.69   0.075       0
#XS Ineff= 2 , 0
       09899.724        10306.56       0
Bank Sta=9499.926,11435.69
Exp/Cntr=0.3,0.1

Type RM Length L Ch R = 1 ,11831.36,245.147500,245.147500,245.147500
XS GIS Cut Line= 6
756456.277642878760553.628285484 757372.47373323 759950.05022215
757688.013207111 759815.09440479757811.528729458759747.366311155
  757942.4346675 759649.32183774758123.678576207759468.376138937
#Sta/Elev= 30
8999.0221277.4689034.0921278.5159066.3421275.1549095.1421274.9549119.5621270.649
9153.4821270.415 9170.911265.5599206.4511265.3349242.2491267.3599301.1811266.886
9325.2561261.2869349.0561252.3089368.9311263.0249372.8561263.168 9461.171260.895
9609.397 1260.079774.0241261.2119892.3751257.2169948.6981260.413   100151258.951
10063.911260.06610177.871267.21110242.491268.72310504.231262.37910580.981263.882
10683.371263.07410774.981266.944 10853.91267.15210871.721271.59411000.921272.399
#Mann= 3 , 0 , 0
8999.022  0.0708       08999.022  0.0708       011000.92  0.0708       0
#XS Ineff= 2 , 0
       09862.635        10283.56       0
Bank Sta=8999.022,11000.92
Exp/Cntr=0.3,0.1

Type RM Length L Ch R = 1 ,11586.21,153.981600,153.981600,153.981600
XS GIS Cut Line= 6
756729.764032753 760880.19433922757001.648707117760639.815678328
757237.553645807760417.654438029757603.673749306760020.474189645
757950.262507672759700.829853746758152.354093792759475.148148613
#Sta/Elev= 30
8999.0191287.5939022.1421286.7659037.3591282.9449052.5771281.2599143.8831277.466
9174.0921277.1229204.1031279.096 9259.131278.4549294.1351267.218 9309.14 1265.56
 9393.741262.9029632.2821263.1069661.0521259.1239869.5991256.2829929.7261253.508
9964.4471255.31710005.971254.452 10019.81256.27910099.531255.06210228.161259.729
 10256.11262.08410499.59  1260.110552.96 1262.6210676.71 1262.78 10774.71267.596
10852.141265.602 10868.91270.22310882.711271.25510987.91 1270.6211000.931271.902
#Mann= 3 , 0 , 0
8999.019  0.0618       08999.019  0.0618       011000.93  0.0618       0
#XS Ineff= 2 , 0
       09875.264        10274.03       0
Bank Sta=8999.019,11000.93
Exp/Cntr=0.3,0.1

Type RM Length L Ch R = 1 ,11432.23,91.166000,91.166000,91.166000
XS GIS Cut Line= 4
756965.825939357760988.635454372757460.617606014760439.156287685
757640.305106014760191.760454357757981.450939327759723.010454372
#Sta/Elev= 30
9054.9991280.6519086.8051279.5149100.2621279.8429140.6321277.4069194.4591275.781
9207.9161274.162 9218.151273.955 9234.831273.7399248.286 1275.019302.1141276.059
9329.0271271.0879367.5911270.5419423.2251266.0859502.0891263.3429561.8651262.161
9606.6971262.451 9611.621262.1059625.0771258.9349636.586 1258.139665.4471258.173
9711.3061259.7769771.0831259.4499801.8791257.5539848.9961256.1519898.434 1252.59
9955.0281253.41510034.391252.95210397.071260.35110567.011261.80210679.931264.621
#Mann= 3 , 0 , 0
9054.999  0.0607       09054.999  0.0607       010679.93  0.0607       0
#XS Ineff= 2 , 0
       09837.387        10240.67       0
Bank Sta=9054.999,10679.93
Exp/Cntr=0.3,0.1

Type RM Length L Ch R = 1 ,11341.07,245.147500,245.147500,245.147500
XS GIS Cut Line= 6
757032.794633415761096.144659893757319.395885453760775.094482542
757563.730854962760466.153527937757642.808944946760348.126991782
757931.105045018759860.191613731758202.041107462759477.858230947
#Sta/Elev= 30
 8999.051282.5669055.0861279.8919068.7051276.9319336.9451273.2649361.6981271.403
9389.8871265.6529442.4981264.5039519.9421260.8299596.4921260.2689612.3081257.168
9724.4521258.3479860.5931256.2279878.0731252.236 9932.551253.2599957.3391252.455
 9980.761248.3059992.3791239.13210003.971237.72210015.531238.756 10029.21250.657
 10050.21254.14210281.341256.91410385.711260.68910503.151260.87110752.351267.989
10843.221264.99410855.631266.13310868.031269.94410921.531268.56411000.981274.757
#Mann= 3 , 0 , 0
 8999.05    0.06       0 8999.05    0.06       011000.98    0.06       0
#XS Ineff= 2 , 0
       0 9879.17        10222.15       0
Bank Sta=8999.05,11000.98
Exp/Cntr=0.3,0.1

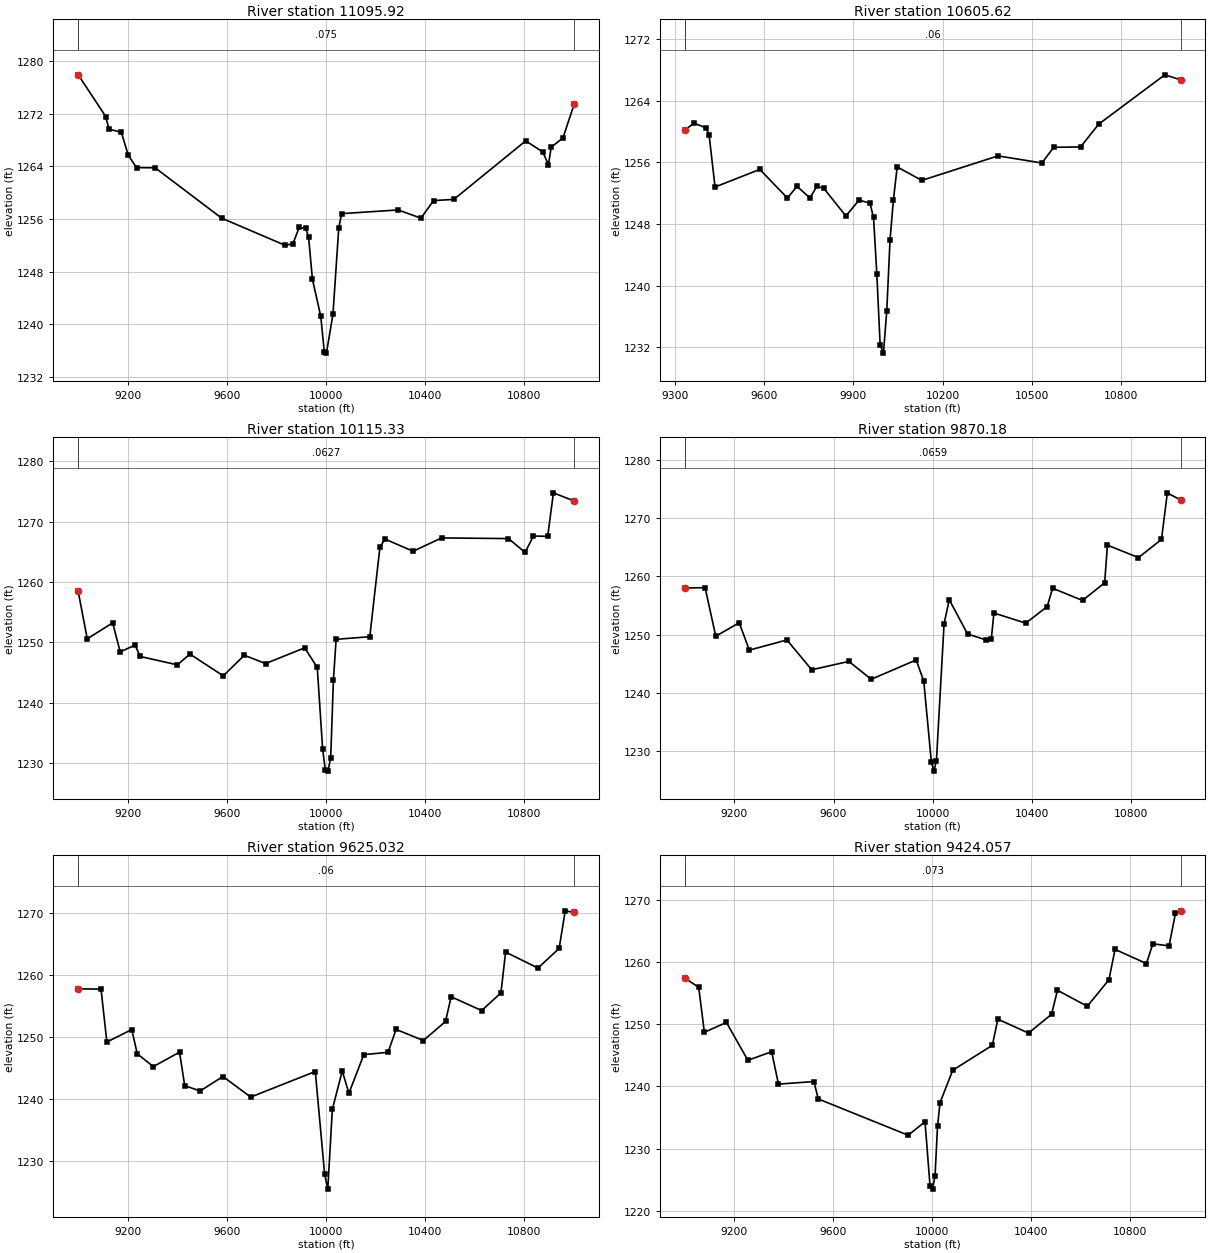
Type RM Length L Ch R = 1 ,11095.92,490.295000,490.295000,490.295000
XS GIS Cut Line= 6
757271.137084367761252.265611156757846.235853069760480.208920678
757925.813120701 760349.76026781757974.808551628760229.303007541
758058.397567536759861.131605898758231.833893532759526.661196857
#Sta/Elev= 30
8999.0471277.9089110.3111271.5619122.8491269.6529172.9991269.1779201.2411265.678
9234.3971263.8019309.5961263.7749578.0831256.1179834.2121251.9929865.7141252.228
9891.247 1254.739917.1341254.5519928.7171253.3139944.4671246.8279978.1211241.198
9992.3311235.794   100011235.59810027.391241.53410050.681254.60510062.321256.804
10290.841257.36710382.431256.11410433.281258.78910515.171258.96810805.291267.867
 10874.11266.18810897.041264.257 10908.51266.92310955.631268.306 11000.9 1273.44
#Mann= 3 , 0 , 0
8999.047   0.075       08999.047   0.075       0 11000.9   0.075       0
#XS Ineff= 2 , 0
       09850.599        10125.79       0
Bank Sta=8999.047,11000.9
Exp/Cntr=0.3,0.1

Type RM Length L Ch R = 1 ,10605.62,490.295100,490.295100,490.295100
XS GIS Cut Line= 6
758465.106062239761176.583725452758418.696107093760773.952917554
758172.742894521 760532.06069812758075.597846779760266.715220304
758076.058360089759937.882779683758173.698228284759667.089475288
#Sta/Elev= 30
9332.2011260.2199364.0771261.0789404.3311260.4919414.3431259.5559434.3671252.801
9584.9851255.085 9677.96 1251.369709.9441252.8889753.7191251.3789776.5591252.875
  9799.41252.6719874.4791249.036  9918.81251.0929955.5231250.7049967.5961248.848
9978.7071241.4539989.8181232.32210000.891231.21910012.041236.657 10023.21245.976
10034.351251.09110047.151255.40610129.981253.65810386.381256.84210533.87 1255.92
10573.89 1257.9610664.191258.002 10725.11260.962 10947.61267.37311000.771266.726
#Mann= 3 , 0 , 0
9332.201    0.06       09332.201    0.06       011000.77    0.06       0
#XS Ineff= 2 , 0
       09929.223        10234.18       0
Bank Sta=9332.201,11000.77
Exp/Cntr=0.3,0.1

Type RM Length L Ch R = 1 ,10115.33,245.147500,245.147500,245.147500
XS GIS Cut Line= 6
758590.934211391761220.134387308758627.915422832761056.320966805
758624.383238528760821.978985267758475.597004964760308.572187823
758659.607007771759702.762996271758853.221229689759322.880566641
#Sta/Elev= 30
8999.2121258.4229035.6481250.575 9138.281253.2169168.6881248.3959228.885 1249.54
9248.9071247.6459399.3431246.2539450.2121248.0359584.5381244.4299669.5441247.838
9755.5981246.4749913.2531249.0749964.0841245.8149985.6081232.362 9996.491228.798
 10007.41228.63110018.331230.88410029.251243.74710040.181250.48510176.041250.915
10217.111265.80410237.64  1267.110350.891265.08510465.551267.29410735.861267.189
10802.681264.90110836.771267.61710894.091267.55410917.291274.77411000.921273.413
#Mann= 3 , 0 , 0
8999.212  0.0627       08999.212  0.0627       011000.92  0.0627       0
#XS Ineff= 2 , 0
       09899.017        10133.33       0
Bank Sta=8999.212,11000.92
Exp/Cntr=0.3,0.1

Type RM Length L Ch R = 1 , 9870.18,245.147500,245.147500,245.147500
XS GIS Cut Line= 6
758585.452997616761319.852106131758689.853539876760980.355592674
758689.542614347760542.766414127758735.588432141760286.765333487
758918.382146387759813.509424333759129.644777091759429.456714166
#Sta/Elev= 30
8999.0481258.0139081.5191258.0629124.5051249.7069219.0821252.0299260.0891247.312
 9411.731249.0699511.7791243.9329661.8761245.3739751.9381242.2899933.4271245.621
9964.0451241.9869994.6641228.13510004.921226.48710015.231228.27910046.181251.886
10067.061255.99510140.791250.095 10215.31249.06610236.651249.18510247.331253.698
10375.931251.95610462.371254.80810484.211257.96710604.951255.86710694.261258.897
10705.531265.38310830.911263.23710923.751266.37310947.311274.38911000.941273.147
#Mann= 3 , 0 , 0
8999.048  0.0659       08999.048  0.0659       011000.94  0.0659       0
#XS Ineff= 2 , 0
       09912.952        10158.15       0
Bank Sta=8999.048,11000.94
Exp/Cntr=0.3,0.1

Type RM Length L Ch R = 1 ,9625.032,200.975300,200.975300,200.975300
XS GIS Cut Line= 6
758617.948789623761354.879762662758777.444629133761023.224135788
758920.011960184760463.755506865758978.162047925760377.606034657
759194.652471011759909.885460809759430.550688189759545.704003018
#Sta/Elev= 30
8999.1271257.7149091.209 1257.679114.7561249.1369215.4091251.1479237.4791247.221
9302.3751245.1679408.0741247.4959428.9681242.1039490.9131241.2259583.1551243.568
9695.4171240.2499956.0271244.3749993.7771227.79110006.481225.39310024.781238.257
 10064.81244.46110091.771240.86610151.94  1247.110249.481247.46810282.191251.166
10392.221249.37710481.661252.44610504.291256.43410627.56 1254.2110705.241257.057
10724.271263.64710854.77 1261.0710940.181264.234 10964.81270.30311000.861270.042
#Mann= 3 , 0 , 0
8999.127    0.06       08999.127    0.06       011000.86    0.06       0
#XS Ineff= 2 , 0
       09911.238        10173.26       0
Bank Sta=8999.127,11000.86
Exp/Cntr=0.3,0.1

Type RM Length L Ch R = 1 ,9424.057,289.319800,289.319800,289.319800
XS GIS Cut Line= 6
758647.610614343761330.479424879759037.746139874760785.832293621
759105.697814776760640.641576559759246.110368599760172.256844445
759417.660462665 759896.91102366759638.364321334759619.451292391
#Sta/Elev= 30
9002.0651257.4369058.7281255.9239081.515 1248.719170.6391250.2889257.0671244.206
9353.2031245.5869380.5361240.379 9523.791240.7939541.1921237.9989904.1431232.168
9972.1931234.3379992.3781224.01110002.47 1223.5110012.581225.617 10022.71233.643
10032.811237.40810084.071242.60810243.961246.61810266.131250.81410389.961248.579
10482.971251.59810506.771255.45710627.251252.88410714.271257.12810739.321262.017
10865.84 1259.7510891.741262.91910957.281262.59210983.211267.86711003.881268.219
#Mann= 3 , 0 , 0
9002.065   0.073       09002.065   0.073       011003.88   0.073       0
#XS Ineff= 2 , 0
       09902.334        10176.53       0
Bank Sta=9002.065,11003.88
Exp/Cntr=0.3,0.1

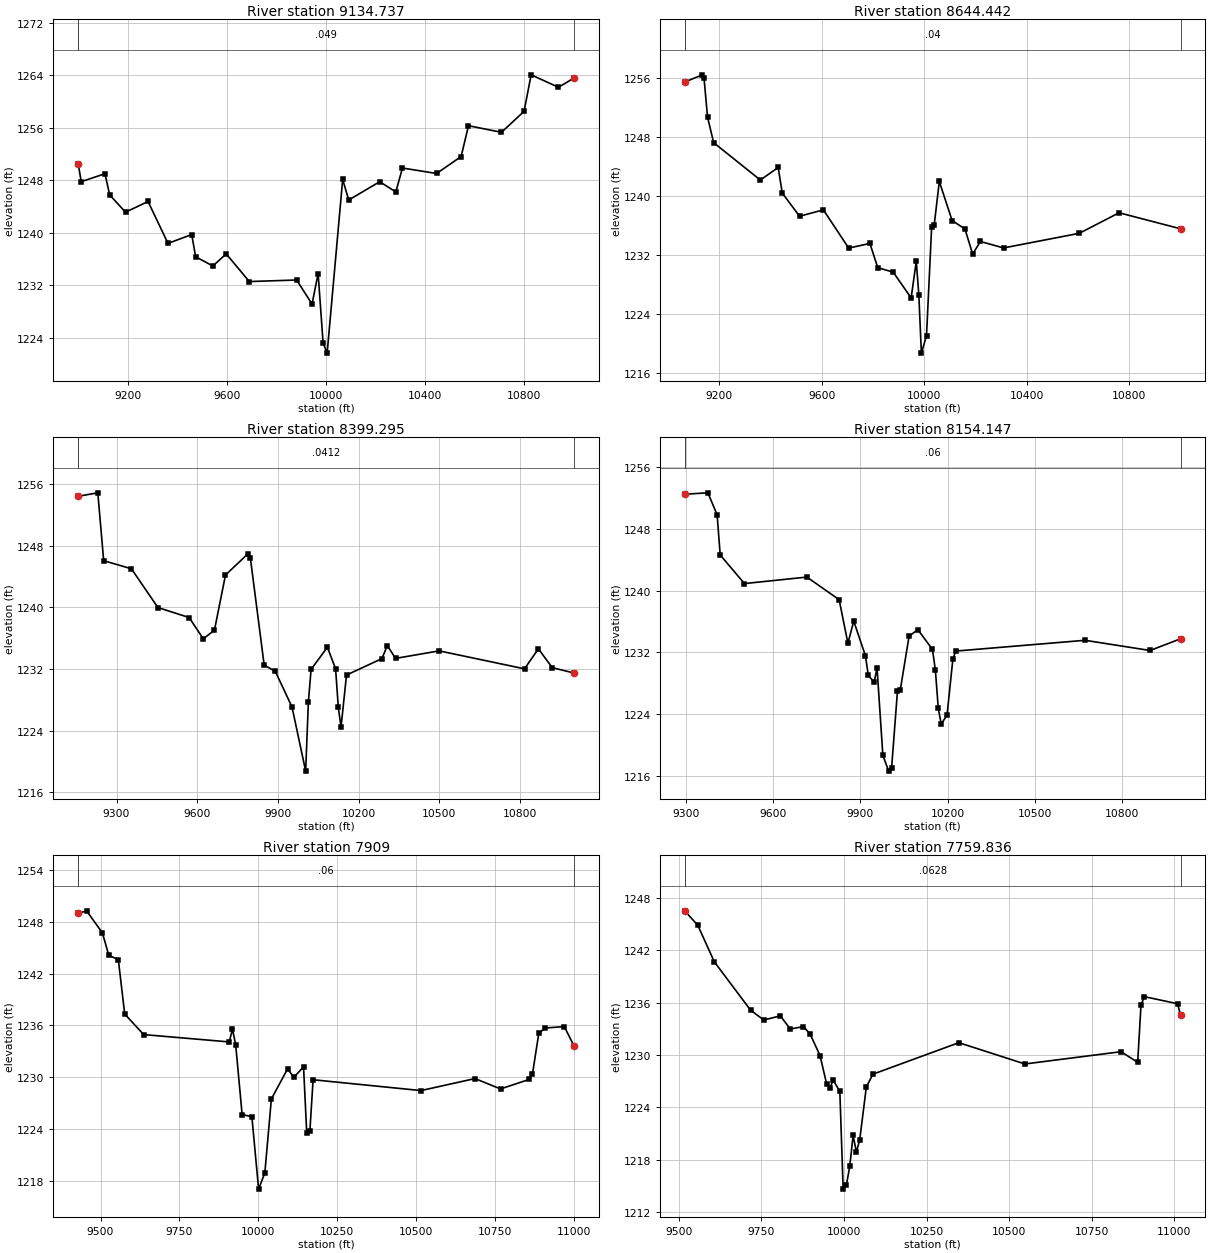
Type RM Length L Ch R = 1 ,9134.737,490.295100,490.295100,490.295100
XS GIS Cut Line= 6
758727.371957421761313.977580884 758994.14253534760995.524391583
759318.420221813760691.897632484759516.195004676760422.160357055
759645.840785909   760273.948466760097.918448075759864.478516488
#Sta/Elev= 30
8999.0561250.5089011.2411247.7929107.0821249.0019125.9851245.7799190.1041243.146
9280.9981244.7749361.4591238.3959457.1841239.7439473.0511236.367 9542.481234.952
 9596.461236.7979689.6711232.5849880.756 1232.829942.9571229.1589967.4311233.809
9987.5421223.24310003.881221.68610066.61 1248.1410090.971244.997   102161247.787
10281.011246.23410307.921249.87110445.721249.03810544.751251.62310574.421256.315
10707.55 1255.31 10798.81258.50610827.241264.06210937.581262.16811000.951263.583
#Mann= 3 , 0 , 0
8999.056   0.049       08999.056   0.049       011000.95   0.049       0
#XS Ineff= 2 , 0
       09891.632        10148.09       0
Bank Sta=8999.056,11000.95
Exp/Cntr=0.3,0.1

Type RM Length L Ch R = 1 ,8644.442,245.147500,245.147500,245.147500
XS GIS Cut Line= 6
758697.189515778761399.740892312758946.358219658761154.248433936
759189.496479351761009.182095153759345.406141276760975.181195404
759886.747348709760938.344169478760464.402342632760783.561461889
#Sta/Elev= 30
9064.611 1255.439134.1171256.4039140.0281255.9989153.8051250.6869177.7311247.203
9360.0261242.1379429.5771243.8389445.7231240.3619513.1611237.2319606.2081238.093
9704.9291232.9099787.8841233.5389818.3771230.2589878.7311229.6469948.8061226.153
9968.8081231.1089978.8091226.569 9988.811218.66610008.811221.04210028.811235.735
10038.81 1236.0410058.81 1241.9410108.831236.63810158.881235.50710188.961232.095
10219.091233.80610309.671232.92910605.351234.91410760.791237.69911000.931235.522
#Mann= 3 , 0 , 0
9064.611    0.04       09064.611    0.04       011000.93    0.04       0
#XS Ineff= 2 , 0
       09927.808         10102.3       0
Bank Sta=9064.611,11000.93
Exp/Cntr=0.3,0.1

Type RM Length L Ch R = 1 ,8399.295,245.147500,245.147500,245.147500
XS GIS Cut Line= 6
758775.339353252761474.884966806758999.232969859761348.176536972
759240.399263137761268.525788777759533.589522035761196.666503018
760086.526754712761109.629511598760543.892556253761003.275618797
#Sta/Elev= 30
9157.5811254.4219230.4121254.8699252.2281246.0559355.2621245.0099453.927 1239.97
 9569.951238.6749622.3861235.9229663.881 1237.029705.0081244.1999787.1481246.909
9797.4151246.4219848.776  1232.5 9890.131231.687 9952.161227.06610002.981218.731
10013.031227.66110023.08 1231.9410083.781234.82210114.211232.01910124.361227.006
 10134.51224.46610154.791231.20810286.35 1233.3410306.591235.03710336.951233.369
10499.261234.34610816.391232.01510867.971234.61210919.551232.16611000.931231.467
#Mann= 3 , 0 , 0
9157.581  0.0412       09157.581  0.0412       011000.93  0.0412       0
#XS Ineff= 2 , 0
       09849.721        10072.79       0
Bank Sta=9157.581,11000.93
Exp/Cntr=0.3,0.1

Type RM Length L Ch R = 1 ,8154.147,245.147500,245.147500,245.147500
XS GIS Cut Line= 6
758870.431774601761566.319987332 759078.35696308 761497.32695402
759284.569420103 761456.20464308759644.486351104761438.154989411
759894.884072211761412.312031916760548.245233893761307.855110298
#Sta/Elev= 30
9296.8211252.5289376.6221252.7079408.3671249.8469418.8981244.6439502.2341240.939
9716.6921241.7819827.5721238.8529857.7181233.204 9877.751236.0669917.8141231.595
9927.8311229.0319947.8441228.1319957.8461229.9869977.8511218.6429997.8571216.615
10007.861217.03710027.881226.94810037.881227.191 10067.91234.11310097.951234.966
10148.131232.40810158.171229.75810168.211224.77110178.241222.70910198.331223.872
10218.471231.18110228.531232.18510672.481233.58210895.85 1232.2611000.971233.779
#Mann= 3 , 0 , 0
9296.821    0.06       09296.821    0.06       011000.97    0.06       0
#XS Ineff= 2 , 0
       09895.138        10120.07       0
Bank Sta=9296.821,11000.97
Exp/Cntr=0.3,0.1

Type RM Length L Ch R = 1 ,    7909,149.163700,149.163700,149.163700
XS GIS Cut Line= 6
759048.775739324761737.804568794759186.994912867761721.091088942
759502.931829286761693.723714646759754.272174902761640.982119114
760265.299017878 761584.03995795760605.660480389761533.500224953
#Sta/Elev= 30
9429.2911248.9539455.7071249.2539506.0711246.7019526.2171244.1079556.4351243.612
9576.5491237.3289636.7461234.9489908.0311234.097 9918.171235.585 9928.311233.771
9948.7131225.7089979.6171225.452   100011217.08310020.791218.97610041.411227.505
10092.571230.96410112.891230.01910143.381231.21310153.461223.59810163.541223.831
10173.621229.72610515.591228.47510686.841229.86410767.611228.66610858.551229.765
10868.671230.33610888.921235.09310909.171235.71110969.921235.86711000.971233.601
#Mann= 3 , 0 , 0
9429.291    0.06       09429.291    0.06       011000.97    0.06       0
#XS Ineff= 2 , 0
       09855.755        10099.71       0
Bank Sta=9429.291,11000.97
Exp/Cntr=0.3,0.1

Type RM Length L Ch R = 1 ,7759.836,341.131400,341.131400,341.131400
XS GIS Cut Line= 6
759115.391607103761801.858287812759286.205999107761798.076966599
759543.611057119761809.826848337760004.888667973761811.262032419
760293.001969129761792.838897098760614.131340133761756.583988102
#Sta/Elev= 30
9517.4871246.5079557.1421244.8569607.1691240.6739717.1841235.1219757.202    1234
 9807.261234.4779837.302 1232.979877.3581233.2449897.3861232.3949927.428 1229.93
9947.4541226.6749957.4551226.2469967.4561227.1029987.4571225.8239997.4871214.627
10007.531215.12810017.571217.27310027.631220.77710037.681218.87910047.68 1220.28
10067.69 1226.32 10087.71227.79510347.861231.40210548.021228.96310839.26 1230.37
10889.571229.15410899.651235.70910909.721236.67711010.471235.86611019.671234.519
#Mann= 3 , 0 , 0
9517.487  0.0628       09517.487  0.0628       011019.67  0.0628       0
#XS Ineff= 2 , 0
       09877.153        10138.47       0
Bank Sta=9517.487,11019.67
Exp/Cntr=0.3,0.1