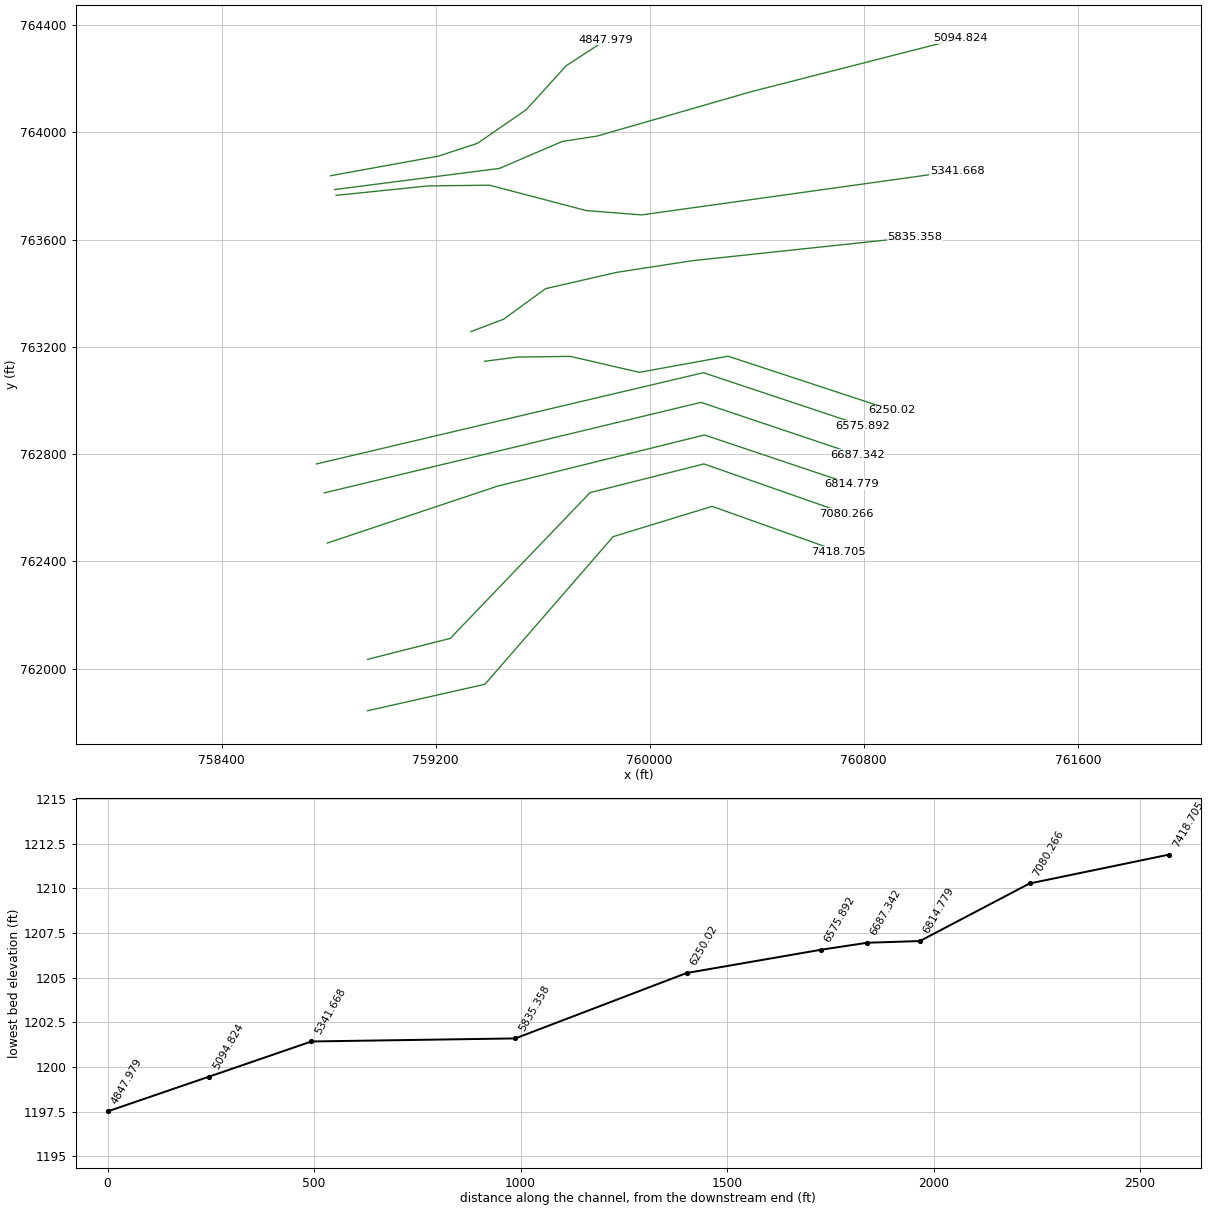
HEC-RAS study 14287_ras.prj: 14287

--- 14287_ras.g01 (geometry) --- (continued)

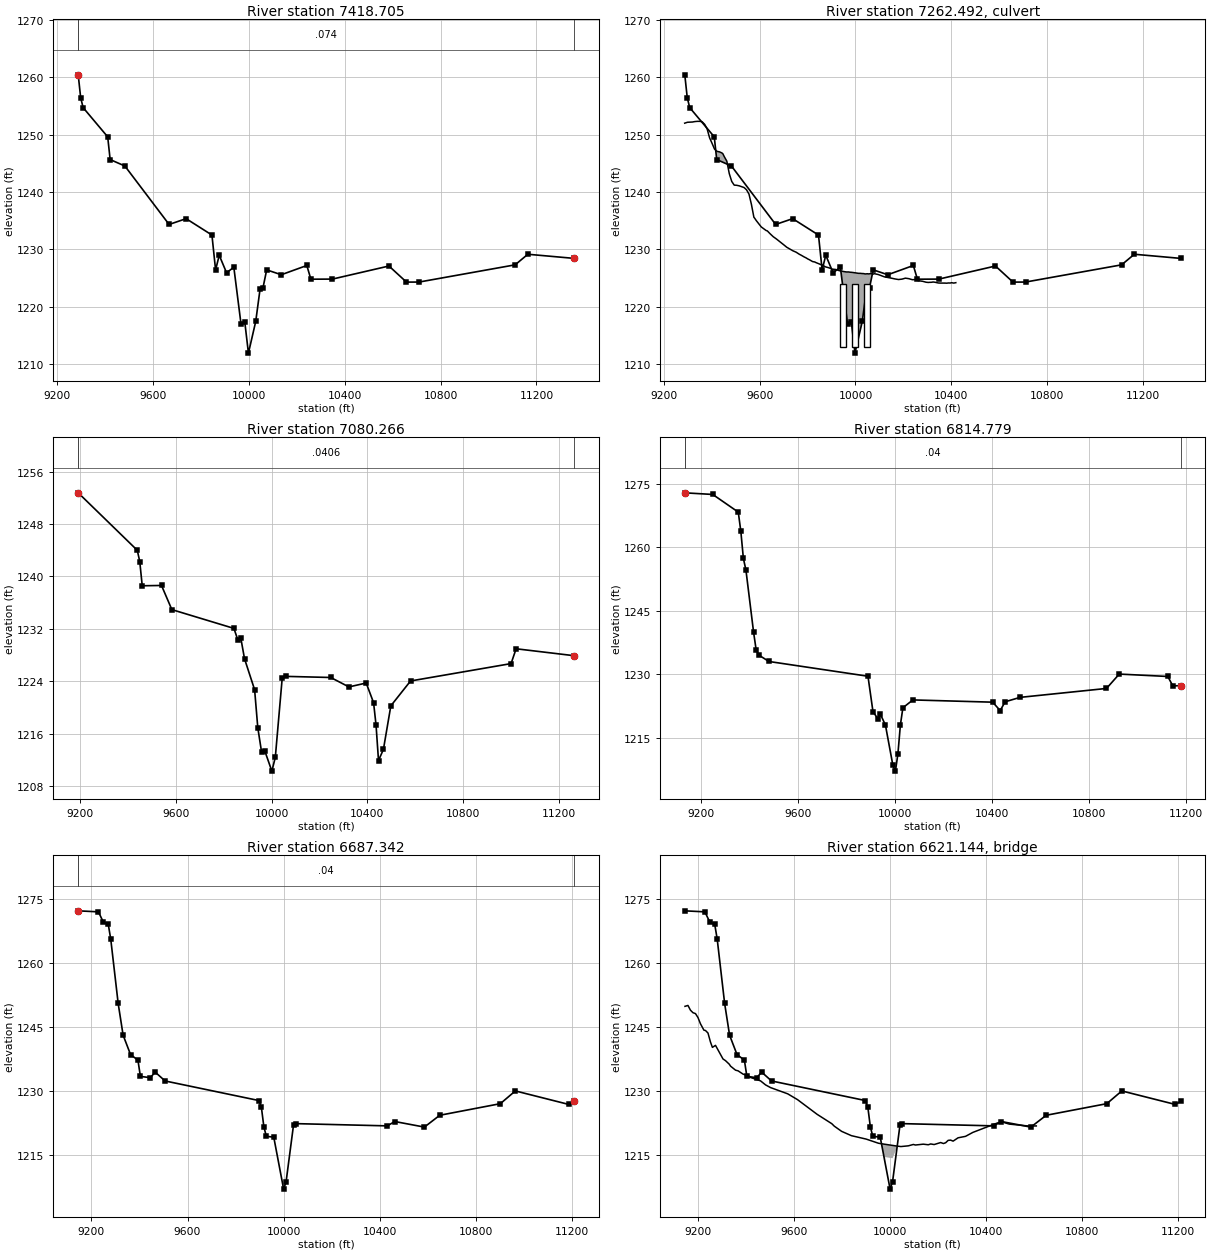
Type RM Length L Ch R = 1 ,7418.705,338.438900,338.438900,338.438900
XS GIS Cut Line= 5
758945.009516925761843.424779072759384.245627999761942.383112386
759863.412294656762492.730334625760233.203961402762605.577556849
760707.040016849762437.181079257
#Sta/Elev= 30
9287.668 1260.419297.9091256.4229308.1591254.6929410.6661249.5969420.9171245.637
 9482.421244.5119666.9321234.3219737.9131235.3339845.6641232.4779860.8931226.395
9876.1221228.9459906.5791225.9099937.0371226.8539966.7891217.0299982.7231217.317
9997.9521211.88810028.411217.41810046.341223.00910058.871223.322 10074.11226.406
10135.011225.55510241.611227.16810258.491224.77810348.211224.795 10584.31227.077
10657.481224.27210709.761224.27811110.871227.28211163.931229.12611357.121228.407
#Mann= 3 , 0 , 0
9287.668   0.074       09287.668   0.074       011357.12   0.074       0
#XS Ineff= 2 , 0
       09915.469         10205.6       0
Bank Sta=9287.668,11357.12
Exp/Cntr=0.3,0.1

Type RM Length L Ch R = 2 ,7262.492,,,
Bridge Culvert--1,0,-1,-1, 0
Deck Dist Width WeirC Skew NumUp NumDn MinLoCord MaxHiCord MaxSubmerge Is_Ogee
119.219,100,2.6,0,157,157, , , 0.95, 0, 0,0,,
 9287.20 9288.56 9298.83 9309.10 9314.07 9319.36 9329.63 9339.90 9350.16 9358.22
 9360.43 9370.70 9380.96 9391.23 9401.50 9402.37 9411.76 9422.03 9432.30 9442.56
 9446.52 9452.83 9463.10 9473.37 9483.63 9490.66 9493.90 9504.17 9514.43 9524.70
 9534.81 9534.97 9545.23 9555.50 9565.77 9576.03 9578.96 9586.30 9596.57 9606.83
 9617.10 9623.11 9627.37 9632.10 9639.99 9643.01 9654.62 9656.71 9669.25 9670.40
 9683.89 9684.10 9697.80 9698.52 9711.50 9713.15 9725.19 9727.79 9738.89 9742.42
 9752.59 9757.05 9766.29 9771.69 9779.98 9786.32 9793.68 9800.95 9807.38 9815.58
 9821.08 9830.22 9834.77 9844.85 9848.47 9859.48 9862.17 9874.12 9875.87 9888.75
 9889.56 9903.26 9903.38 9916.96 9918.02 9930.66 9932.65 9944.35 9947.28 9958.05
 9961.92 9971.75 9976.55 9985.45 9991.18 9999.1410005.8110012.8410020.4510026.54
10035.0810040.2410049.7110053.9310064.3510067.6310072.4910078.8810081.4610093.28
10095.3510107.6810109.2510122.0810123.1510136.4810137.0410150.8910150.9410164.83
10165.2910178.7310179.6910192.6310194.0910206.5210208.4910220.4210222.8910234.31
10237.3010248.2110251.7010262.1110266.1010276.0010280.5010289.9010294.9010303.79
10309.3010317.6910323.7110331.5910338.1110345.4810352.5110359.3810366.9110373.28
10381.3110387.1710395.7210401.0710410.1210414.9610418.83
 1251.98 1252.00 1252.14 1252.16 1252.16 1252.18 1252.26 1252.30 1252.30 1252.25
 1252.21 1251.77 1250.97 1249.42 1248.47 1248.38 1247.46 1247.07 1246.98 1246.79
 1246.65 1246.12 1245.36 1243.18 1241.82 1241.36 1241.18 1241.15 1241.06 1240.90
 1240.76 1240.76 1240.37 1239.63 1237.82 1235.58 1235.43 1234.98 1234.43 1233.89
 1233.56 1233.39 1233.26 1233.20 1232.86 1232.73 1232.26 1232.19 1231.82 1231.78
 1231.32 1231.31 1230.87 1230.85 1230.41 1230.35 1230.06 1230.00 1229.73 1229.67
 1229.48 1229.36 1229.11 1229.00 1228.79 1228.65 1228.50 1228.31 1228.18 1227.97
 1227.85 1227.78 1227.68 1227.51 1227.44 1227.26 1227.25 1226.94 1226.92 1226.77
 1226.76 1226.53 1226.53 1226.47 1226.47 1226.29 1226.26 1226.19 1226.14 1226.08
 1226.04 1226.04 1226.00 1225.97 1225.93 1225.89 1225.85 1225.80 1225.80 1225.77
 1225.75 1225.69 1225.73 1225.70 1225.75 1225.73 1225.65 1225.74 1225.72 1225.61
 1225.59 1225.39 1225.37 1225.17 1225.17 1225.07 1225.07 1224.95 1224.95 1224.82
 1224.82 1224.72 1224.72 1224.78 1224.79 1224.93 1224.96 1224.89 1224.87 1224.72
 1224.69 1224.71 1224.65 1224.52 1224.50 1224.45 1224.41 1224.30 1224.25 1224.21
 1224.23 1224.24 1224.29 1224.25 1224.19 1224.12 1224.10 1224.10 1224.11 1224.10
 1224.08 1224.12 1224.11 1224.17 1224.10 1224.13 1224.17
                                                                                
                                                                                
                                                                                
                                                                                
                                                                                
                                                                                
                                                                                
                                                                                
                                                                                
                                                                                
                                                                                
                                                                                
                                                                                
                                                                                
                                                                                
                                                        
 9287.20 9288.56 9298.83 9309.10 9314.07 9319.36 9329.63 9339.90 9350.16 9358.22
 9360.43 9370.70 9380.96 9391.23 9401.50 9402.37 9411.76 9422.03 9432.30 9442.56
 9446.52 9452.83 9463.10 9473.37 9483.63 9490.66 9493.90 9504.17 9514.43 9524.70
 9534.81 9534.97 9545.23 9555.50 9565.77 9576.03 9578.96 9586.30 9596.57 9606.83
 9617.10 9623.11 9627.37 9632.10 9639.99 9643.01 9654.62 9656.71 9669.25 9670.40
 9683.89 9684.10 9697.80 9698.52 9711.50 9713.15 9725.19 9727.79 9738.89 9742.42
 9752.59 9757.05 9766.29 9771.69 9779.98 9786.32 9793.68 9800.95 9807.38 9815.58
 9821.08 9830.22 9834.77 9844.85 9848.47 9859.48 9862.17 9874.12 9875.87 9888.75
 9889.56 9903.26 9903.38 9916.96 9918.02 9930.66 9932.65 9944.35 9947.28 9958.05
 9961.92 9971.75 9976.55 9985.45 9991.18 9999.1410005.8110012.8410020.4510026.54
10035.0810040.2410049.7110053.9310064.3510067.6310072.4910078.8810081.4610093.28
10095.3510107.6810109.2510122.0810123.1510136.4810137.0410150.8910150.9410164.83
10165.2910178.7310179.6910192.6310194.0910206.5210208.4910220.4210222.8910234.31
10237.3010248.2110251.7010262.1110266.1010276.0010280.5010289.9010294.9010303.79
10309.3010317.6910323.7110331.5910338.1110345.4810352.5110359.3810366.9110373.28
10381.3110387.1710395.7210401.0710410.1210414.9610418.83
 1251.98 1252.00 1252.14 1252.16 1252.16 1252.18 1252.26 1252.30 1252.30 1252.25
 1252.21 1251.77 1250.97 1249.42 1248.47 1248.38 1247.46 1247.07 1246.98 1246.79
 1246.65 1246.12 1245.36 1243.18 1241.82 1241.36 1241.18 1241.15 1241.06 1240.90
 1240.76 1240.76 1240.37 1239.63 1237.82 1235.58 1235.43 1234.98 1234.43 1233.89
 1233.56 1233.39 1233.26 1233.20 1232.86 1232.73 1232.26 1232.19 1231.82 1231.78
 1231.32 1231.31 1230.87 1230.85 1230.41 1230.35 1230.06 1230.00 1229.73 1229.67
 1229.48 1229.36 1229.11 1229.00 1228.79 1228.65 1228.50 1228.31 1228.18 1227.97
 1227.85 1227.78 1227.68 1227.51 1227.44 1227.26 1227.25 1226.94 1226.92 1226.77
 1226.76 1226.53 1226.53 1226.47 1226.47 1226.29 1226.26 1226.19 1226.14 1226.08
 1226.04 1226.04 1226.00 1225.97 1225.93 1225.89 1225.85 1225.80 1225.80 1225.77
 1225.75 1225.69 1225.73 1225.70 1225.75 1225.73 1225.65 1225.74 1225.72 1225.61
 1225.59 1225.39 1225.37 1225.17 1225.17 1225.07 1225.07 1224.95 1224.95 1224.82
 1224.82 1224.72 1224.72 1224.78 1224.79 1224.93 1224.96 1224.89 1224.87 1224.72
 1224.69 1224.71 1224.65 1224.52 1224.50 1224.45 1224.41 1224.30 1224.25 1224.21
 1224.23 1224.24 1224.29 1224.25 1224.19 1224.12 1224.10 1224.10 1224.11 1224.10
 1224.08 1224.12 1224.11 1224.17 1224.10 1224.13 1224.17
                                                                                
                                                                                
                                                                                
                                                                                
                                                                                
                                                                                
                                                                                
                                                                                
                                                                                
                                                                                
                                                                                
                                                                                
                                                                                
                                                                                
                                                                                
                                                        
BR Coef=-1 , 0 , 0 ,, 0 ,,,0.8,-1,,0,
WSPro=,,,, 1 ,,,, 0 ,,,, 0 ,,,,-1 ,-1 ,-1 , 0 , 0 , 0 , 0 , 0
Multiple Barrel Culv=2,11,25,100,0.013,0.4,1,58,1,1212.99,1210.83,3,Culvert #1, 0, 119.219
 9950.00 9950.0010000.0010000.0010050.0010050.00
Culvert Bottom n=0.013
BC Design=,, 0 ,, 0 ,,,,,,

Type RM Length L Ch R = 1 ,7080.266,265.487200,265.487200,265.487200
XS GIS Cut Line= 5
758945.400141895 762035.20718646759254.427919626 762113.33218646
759776.997364104762656.734964237760202.691808552762763.679408699
760734.154735589762577.838682709
#Sta/Elev= 30
9190.5681252.7629437.7061243.9869448.0211242.2659458.335 1238.579538.9971238.617
9582.277 1234.93 9841.961232.0619858.4741230.2799870.8131230.5619886.2221227.433
 9928.521222.6929941.7161216.9169957.374 1213.239971.8011213.27510000.651210.268
10015.081212.38210043.931224.48510058.361224.73610246.941224.56610323.021223.124
 10395.21223.72210426.131220.71710436.441217.30410446.751211.88210467.371213.603
10498.311220.23710580.791224.03411001.211226.687 11022.4 1228.9511265.161227.892
#Mann= 3 , 0 , 0
9190.568  0.0406       09190.568  0.0406       011265.16  0.0406       0
#XS Ineff= 2 , 0
       09825.466         10108.3       0
Bank Sta=9190.568,11265.16
Exp/Cntr=0.3,0.1

Type RM Length L Ch R = 1 ,6814.779,127.436900,127.436900,127.436900
XS GIS Cut Line= 4
758795.052919686762468.887742013759430.469586343 762680.69329758
760204.775141895762871.665519819760755.264029494762687.343144835
#Sta/Elev= 30
9130.8161272.936 9246.711272.551 9352.12 1268.379362.6611263.8329373.2021257.405
9383.7421254.6539415.3651239.9229425.9061235.7699436.4471234.5419478.6111233.005
9887.6671229.5119908.2671221.1529928.866  1219.49939.1661220.4929959.7651217.948
9990.6641208.37810000.961207.04510011.261211.12710021.561217.98810031.861222.045
10073.061223.90410402.65 1223.3710433.551221.38710454.151223.46710515.95 1224.51
10872.54 1226.6210925.271230.02411125.631229.45511146.721227.20411178.641227.305
#Mann= 3 , 0 , 0
9130.816    0.04       09130.816    0.04       011178.64    0.04       0
#XS Ineff= 2 , 0
       0                10165.08       0
Bank Sta=9130.816,11178.64
Exp/Cntr=0.3,0.1

Type RM Length L Ch R = 1 ,6687.342,111.449100,111.449100,111.449100
XS GIS Cut Line= 3
758783.189493775 762655.69329758760191.522827089 762993.19329758
760776.441391605762797.200710776
#Sta/Elev= 30
9144.7461272.1289228.8731271.889 9249.441269.4789270.0061268.9279280.289 1265.46
9311.1381250.4279331.7051243.0089362.5541238.4799393.4041237.1519403.6871233.351
9444.8191233.0539465.3861234.3489506.5181232.2829897.2771227.6959907.5611226.076
9917.8441221.5349928.1271219.3089958.9761219.13410000.11 1206.9510010.39 1208.69
10041.241221.95110051.521222.289   104321221.76310462.851222.78610586.251221.477
10650.221224.24810902.471226.96410964.971229.94811187.221226.78911209.841227.479
#Mann= 3 , 0 , 0
9144.746    0.04       09144.746    0.04       011209.84    0.04       0
#XS Ineff= 2 , 0
       09875.758        10072.91       0
Bank Sta=9144.746,11209.84
Exp/Cntr=0.3,0.1

Type RM Length L Ch R = 3 ,6621.144,,,
BEGIN DESCRIPTION:
END DESCRIPTION:
Bridge Culvert--1,0,-1,-1, 0
Deck Dist Width WeirC Skew NumUp NumDn MinLoCord MaxHiCord MaxSubmerge Is_Ogee
43.421450,24.606200,2.6,0, 60, 60, , , 0.95, 0, 0,0,,
 9146.04 9158.37 9168.80 9179.22 9189.65 9200.08 9210.50 9224.80 9231.35 9241.78
 9252.21 9260.13 9273.06 9304.34 9314.76 9330.80 9335.62 9356.47 9366.90 9387.75
 9408.60 9419.03 9460.73 9481.58 9502.32 9573.75 9614.57 9696.21 9757.44 9767.64
 9798.26 9839.08 9900.31 9951.99 9979.32 9979.3210029.1810029.1810045.1210076.17
10096.8610105.6610138.2610158.9510169.3010183.4010210.6910222.2810231.3910241.74
10252.0910262.4410283.1310314.1810344.8210445.7610465.9510496.2410576.9910608.91
 1249.76 1249.97 1248.86 1248.27 1248.06 1247.14 1245.67 1244.18 1244.10 1243.51
 1241.39 1240.15 1240.62 1237.43 1237.04 1236.18 1235.76 1234.81 1234.66 1233.89
 1233.49 1233.10 1232.30 1231.36 1230.73 1229.27 1227.91 1224.47 1222.27 1221.70
 1220.48 1219.47 1218.67 1217.69 1217.45 1217.45 1217.03 1217.03 1216.92 1217.09
 1217.41 1217.28 1217.48 1217.34 1217.53 1217.39 1217.86 1217.63 1217.81 1218.37
 1218.43 1218.19 1218.97 1219.31 1220.24 1222.42 1222.70 1222.18 1221.73 1221.75
  249.76  249.97  248.86  248.27  248.06  247.14  245.67  244.18  244.10  243.51
  241.39  240.15  240.62  237.43  237.04  236.18  235.76  234.81  234.66  233.89
  233.49  233.10  232.30  231.36  230.73  229.27  227.91  224.47  222.27  221.70
  220.48  219.47  218.67  217.69  217.45 1214.45 1214.03  217.03  216.92  217.09
  217.41  217.28  217.48  217.34  217.53  217.39  217.86  217.63  217.81  218.37
  218.43  218.19  218.97  219.31  220.24  222.42  222.70  222.18  221.73  221.75
 9146.04 9158.37 9168.80 9179.22 9189.65 9200.08 9210.50 9224.80 9231.35 9241.78
 9252.21 9260.13 9273.06 9304.34 9314.76 9330.80 9335.62 9356.47 9366.90 9387.75
 9408.60 9419.03 9460.73 9481.58 9502.32 9573.75 9614.57 9696.21 9757.44 9767.64
 9798.26 9839.08 9900.31 9951.99 9980.85 9980.8510030.7110030.7110045.1210076.17
10096.8610105.6610138.2610158.9510169.3010183.4010210.6910222.2810231.3910241.74
10252.0910262.4410283.1310314.1810344.8210445.7610465.9510496.2410576.9910608.91
 1249.76 1249.97 1248.86 1248.27 1248.06 1247.14 1245.67 1244.18 1244.10 1243.51
 1241.39 1240.15 1240.62 1237.43 1237.04 1236.18 1235.76 1234.81 1234.66 1233.89
 1233.49 1233.10 1232.30 1231.36 1230.73 1229.27 1227.91 1224.47 1222.27 1221.70
 1220.48 1219.47 1218.67 1217.69 1217.44 1217.44 1217.02 1217.02 1216.92 1217.09
 1217.41 1217.28 1217.48 1217.34 1217.53 1217.39 1217.86 1217.63 1217.81 1218.37
 1218.43 1218.19 1218.97 1219.31 1220.24 1222.42 1222.70 1222.18 1221.73 1221.75
  249.76  249.97  248.86  248.27  248.06  247.14  245.67  244.18  244.10  243.51
  241.39  240.15  240.62  237.43  237.04  236.18  235.76  234.81  234.66  233.89
  233.49  233.10  232.30  231.36  230.73  229.27  227.91  224.47  222.27  221.70
  220.48  219.47  218.67  217.69  217.44 1214.44 1214.02  217.02  216.92  217.09
  217.41  217.28  217.48  217.34  217.53  217.39  217.86  217.63  217.81  218.37
  218.43  218.19  218.97  219.31  220.24  222.42  222.70  222.18  221.73  221.75
BR Coef=-1 , 0 , 0 ,, 0 ,,,0.8,0,1,0,
WSPro=,,,, 1 ,,,, 0 ,,,, 0 ,,,,-1 ,-1 ,-1 , 0 , 0 , 0 , 0 , 0
BC Design=,, 0 ,, 0 ,,,,,,

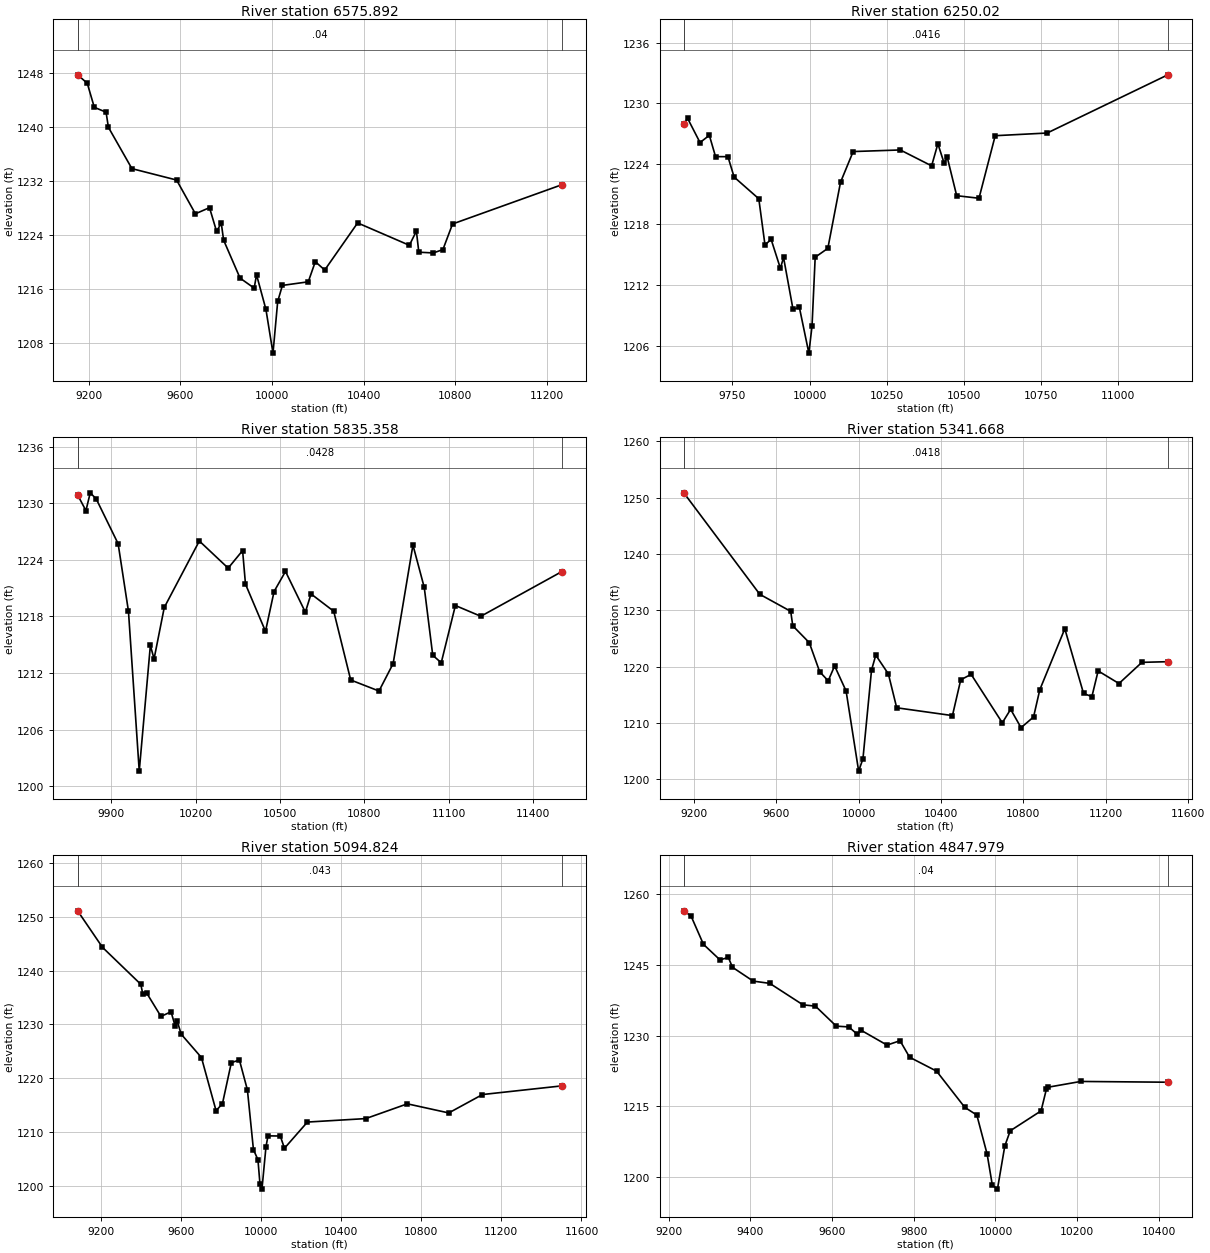
Type RM Length L Ch R = 1 ,6575.892,325.872800,325.872800,325.872800
XS GIS Cut Line= 3
758754.022827089762763.609964237760200.391461372763103.841445729
760797.331391637762905.567585933
#Sta/Elev= 30
9150.5461247.6899192.6421246.4469223.4611242.8869274.8251242.1699285.0981239.932
9387.8281233.8249583.0141232.1419665.197 1227.159726.8351228.0599757.6541224.556
  9778.21225.7649788.4731223.2579860.3831217.6439922.0211216.1679932.2941218.142
9973.3861213.015 10004.2 1206.5610024.751214.194 10045.31216.569 10158.31217.099
10189.121220.07510230.211218.84110374.031225.80210600.041222.49810630.851224.599
10641.251221.47710704.471221.36610746.621221.86110788.771225.647 11265.41231.435
#Mann= 3 , 0 , 0
9150.546    0.04       09150.546    0.04       0 11265.4    0.04       0
#XS Ineff= 2 , 0
       09892.069        10084.85       0
Bank Sta=9150.546,11265.4
Exp/Cntr=0.3,0.1

Type RM Length L Ch R = 1 , 6250.02,414.661700,414.661700,414.661700
XS GIS Cut Line= 6
759382.946942773763146.337541565759504.124364475763162.087507295
759703.519353629763164.657831161759961.326720566763105.139649644
760292.728116602763165.394448921760906.863570839762963.772620544
#Sta/Elev= 30
9592.1541227.9239604.3361228.5199644.7511226.1169674.9621226.8339695.1031224.722
9735.2681224.7179755.2971222.6999835.3761220.5489855.389 1215.989875.4011216.519
9905.4281213.6549915.6291214.7379946.4181209.5869966.9441209.7939997.7331205.255
   100081207.93410018.261214.75510059.311215.63710100.361222.17810141.421225.224
10294.241225.38210395.871223.808 10416.21225.99510436.531224.06810446.691224.641
10477.191220.851 10549.51220.59810602.121226.79510770.531227.05911161.921232.825
#Mann= 3 , 0 , 0
9592.154  0.0416       09592.154  0.0416       011161.92  0.0416       0
#XS Ineff= 2 , 0
       0                               0
Bank Sta=9592.154,11161.92
Exp/Cntr=0.3,0.1

Type RM Length L Ch R = 1 ,5835.358,493.689600,493.689600,493.689600
XS GIS Cut Line= 6
759331.872176264763257.207156664759453.975924867763303.267310906
 759610.70775381763417.229753335759877.134631611763478.055367052
760159.457421223763521.424629675760990.515193455763609.762005059
#Sta/Elev= 30
9780.6371230.8849810.1911229.2179825.4781231.1079846.6611230.4659924.6481225.707
9961.3571218.5449999.6581201.59310039.181214.92110052.361213.49610088.581218.947
10213.221225.99910315.69 1223.1210366.991224.98210377.251221.42510448.371216.421
10478.84 1220.6410519.441222.77110590.051218.44910610.221220.38510690.83 1218.55
10751.171211.25810851.731210.08810902.021212.99510972.411225.56911012.641221.068
 11042.81213.87911072.971213.08911123.261219.15611213.761218.01511500.891222.741
#Mann= 3 , 0 , 0
9780.637  0.0428       09780.637  0.0428       011500.89  0.0428       0
#XS Ineff= 2 , 0
       0                10259.97       0
Bank Sta=9780.637,11500.89
Exp/Cntr=0.3,0.1

Type RM Length L Ch R = 1 ,5341.668,246.844800,246.844800,246.844800
XS GIS Cut Line= 6
758827.897156497763765.019199218759172.533252239763800.224705952
759401.327616041763802.893659524759762.545061172763708.242407917
759970.020023302763692.131721022761149.432647507763856.343562138
#Sta/Elev= 30
9150.988 1250.879519.9751232.8379670.0491229.8159680.0561227.2439760.2291224.247
9810.7471219.075 9851.99 1217.47 9883.291220.1169938.9641215.6559999.9151201.422
10020.761203.62410062.391219.36410083.031222.02710144.291218.68610184.631212.677
10455.261211.28910495.521217.64710545.961218.61810697.331210.00910737.791212.401
10788.371209.14310849.061211.04510879.411215.888 11000.81226.71411091.841215.216
 11132.31214.66511162.641219.229 11263.81216.98811375.071220.74911500.941220.868
#Mann= 3 , 0 , 0
9150.988  0.0418       09150.988  0.0418       011500.94  0.0418       0
#XS Ineff= 2 , 0
       0                10127.36       0
Bank Sta=9150.988,11500.94
Exp/Cntr=0.3,0.1

Type RM Length L Ch R = 1 ,5094.824,246.844800,246.844800,246.844800
XS GIS Cut Line= 6
758821.892899367763786.662451662759438.197336392763865.423415155
759672.886449743763965.855327799759803.608187252763986.020275452
760379.100341164764151.383263089761161.518160635764350.839945141
#Sta/Elev= 30
9084.2671251.084 9208.471244.3099399.8041237.4529409.8661235.6139429.9881235.779
9500.4181231.4929550.7251232.3639570.8481229.7669580.9091230.7179601.0541228.217
9702.4921223.8719775.4691214.0159807.4141215.3149851.7951222.9279892.0941223.412
 9932.031217.8629962.1821206.7759984.623 1204.929994.6441200.44510004.67 1199.46
10024.771207.33410034.811209.34110096.141209.31310116.981207.04210231.611211.901
10523.141212.545 10730.61215.28210937.341213.59511105.751217.00711500.941218.609
#Mann= 3 , 0 , 0
9084.267   0.043       09084.267   0.043       011500.94   0.043       0
#XS Ineff= 2 , 0
       0                 10129.1       0
Bank Sta=9084.267,11500.94
Exp/Cntr=0.3,0.1

Type RM Length L Ch R = 1 ,4847.979,246.844900,246.844900,246.844900
XS GIS Cut Line= 6
758807.585527275763838.235537109759210.616001455763911.308309037
759356.216650378 763959.00640824759538.371998911764084.247141102
759687.794175779764248.320524907759836.480897005764344.648752554
#Sta/Elev= 30
9237.0711256.4199254.7381255.3339285.1741249.3229325.7551246.0279346.0461246.561
9356.1911244.4689406.9181241.5399447.4991241.0639528.6621236.5239559.2891236.239
 9610.351232.0059640.9871231.8449661.6041230.2889671.951 1231.099734.5211227.996
9766.3561228.9249789.7231225.4299855.7261222.4879924.7811214.8199954.3291213.184
9979.5641204.9069992.1821198.38510004.791197.50410022.771206.62710036.07 1209.85
10111.58 1214.0710124.771218.72910129.051219.08410208.741220.29910421.821220.136
#Mann= 3 , 0 , 0
9237.071    0.04       09237.071    0.04       010421.82    0.04       0
#XS Ineff= 2 , 0
       0                               0
Bank Sta=9237.071,10421.82
Exp/Cntr=0.3,0.1