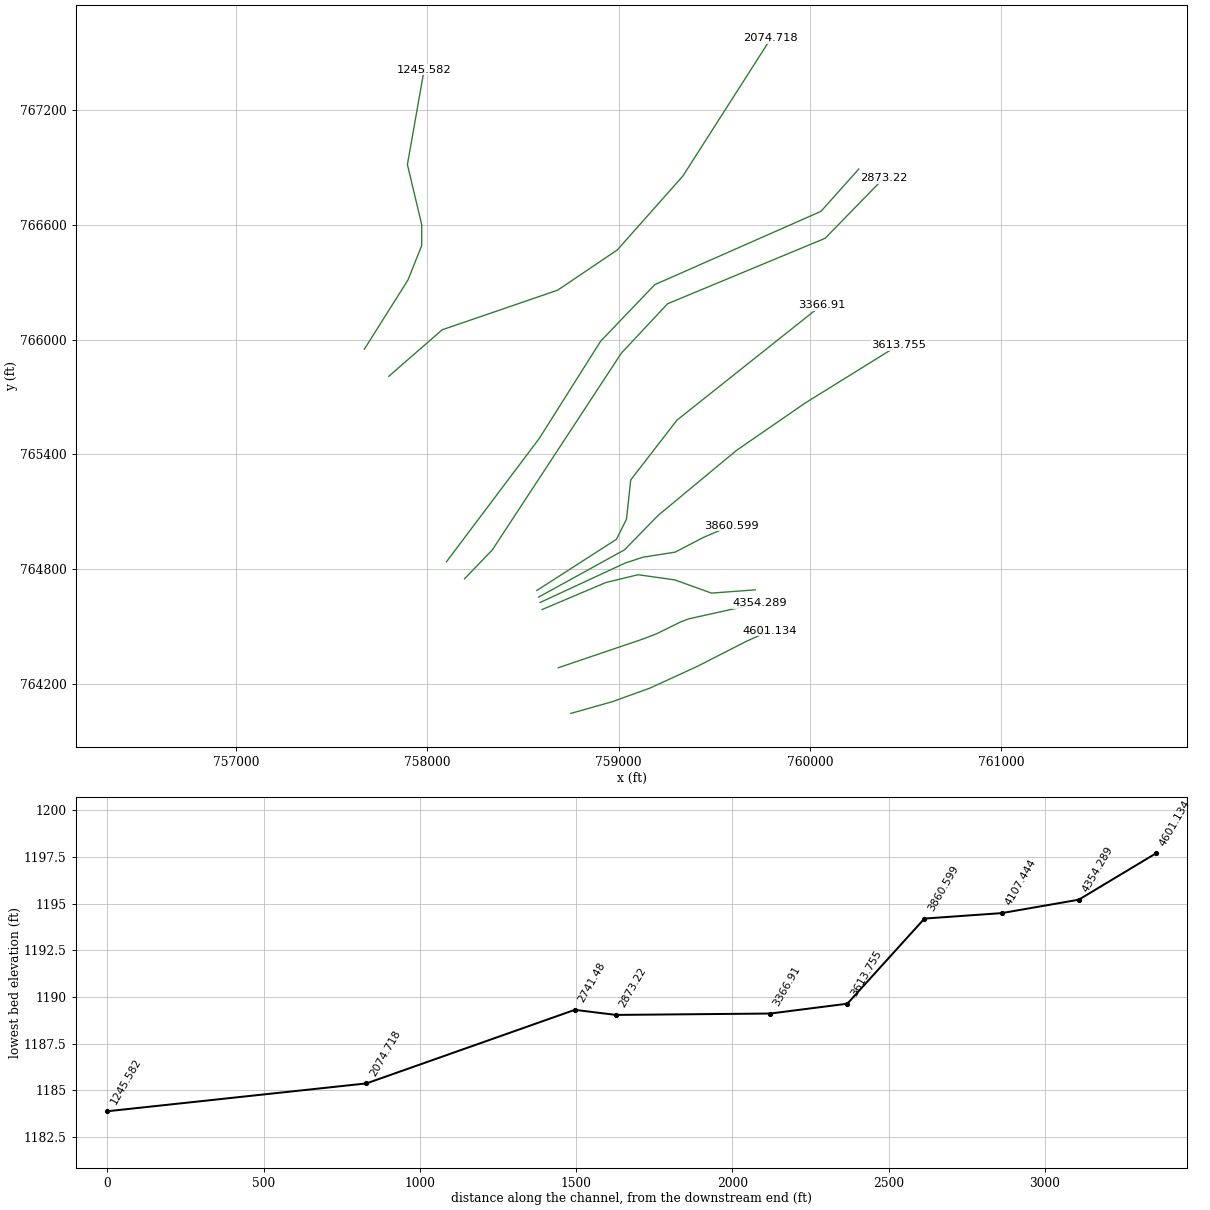
HEC-RAS study 14287_ras.prj: 14287

--- 14287_ras.g01 (geometry) --- (continued)

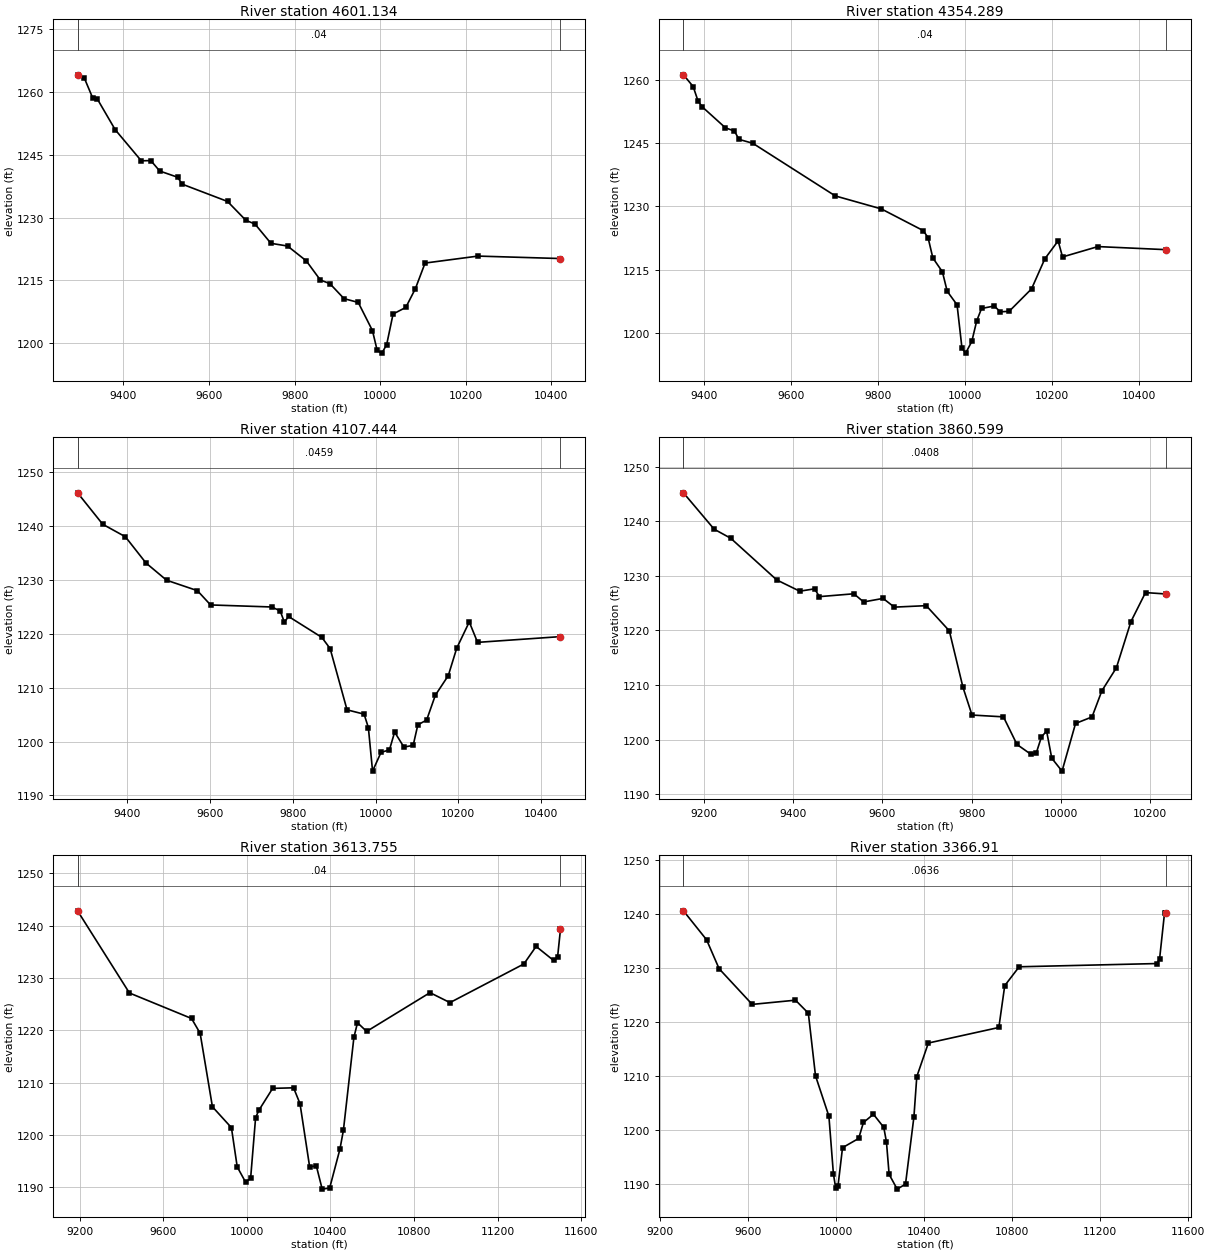
Type RM Length L Ch R = 1 ,4601.134,246.844800,246.844800,246.844800
XS GIS Cut Line= 6
758750.012834921764045.765009542758966.695360966764106.865880877
759163.733486833764178.097034771759412.375740947764292.260481349
759669.424151236 764423.53317264759789.448226501764477.402257986
#Sta/Elev= 30
9292.6531263.9869308.1681263.287 9328.36 1258.399339.2251258.1629380.6341250.911
9441.6251243.5079463.8441243.5589484.7221241.0729526.5611239.5949537.0991237.948
9643.1171233.8279685.924 1229.349707.3271228.4429744.5151223.8559783.385 1223.21
9827.0851219.6879860.049 1215.119882.1821214.2649915.3831210.6799948.5831209.775
9981.783 1203.07 9992.851198.34710003.921197.70110015.051199.748   100301207.017
10059.76 1208.5910082.251213.07810104.741219.15310228.441220.81510421.211220.228
#Mann= 3 , 0 , 0
9292.653    0.04       09292.653    0.04       010421.21    0.04       0
#XS Ineff= 2 , 0
       0                               0
Bank Sta=9292.653,10421.21
Exp/Cntr=0.3,0.1

Type RM Length L Ch R = 1 ,4354.289,246.844800,246.844800,246.844800
XS GIS Cut Line= 6
758683.836322751764284.308251078759129.142941329764435.327873479
759200.145063934764462.887535782759322.131407109764523.291872816
759364.529930634764539.664768129759738.064858714 764622.43595736
#Sta/Elev= 30
 9351.911261.2049374.2311258.4289385.5471254.9779395.3251253.5949448.4691248.639
9469.1541247.8759479.7011245.8979511.3911244.9789701.1871232.4929807.142 1229.41
9903.628 1224.26  9914.61222.5819925.5731217.7939947.518  1214.59958.605 1209.88
9981.2571206.6749992.5831196.384   10001 1195.2210015.181197.99110026.451202.853
10037.561205.80510066.991206.39810080.421205.01610101.051205.12810152.641210.463
10183.191217.58410213.711221.83310223.891218.02710305.281220.481 10462.71219.748
#Mann= 3 , 0 , 0
 9351.91    0.04       0 9351.91    0.04       0 10462.7    0.04       0
#XS Ineff= 2 , 0
       0                               0
Bank Sta=9351.91,10462.7
Exp/Cntr=0.3,0.1

Type RM Length L Ch R = 1 ,4107.444,246.844800,246.844800,246.844800
XS GIS Cut Line= 6
758599.403735037764588.658276549758933.147240301764730.151199426
759101.153573397764770.702667263759292.534440854764743.835741008
759484.928106207 764674.57469823759713.542669129764691.651815047
#Sta/Elev= 30
9280.5681246.1739341.2741240.3399395.9621238.0219445.7641233.1479495.5651229.946
9569.8941228.0119601.7341225.3579749.3441224.9799769.7861224.2549779.9791222.152
9790.0551223.214 9870.311219.3419890.4271217.2549931.2671205.881 9972.461205.078
9982.7581202.5869992.9121194.50210013.341197.98410033.651198.44810046.211201.745
10068.581198.97110090.941199.27910102.211203.09110123.491203.989 10144.51208.595
10175.76 1212.2410196.071217.31710226.41  1222.210246.451218.40910446.661219.476
#Mann= 3 , 0 , 0
9280.568  0.0459       09280.568  0.0459       010446.66  0.0459       0
#XS Ineff= 2 , 0
       0                               0
Bank Sta=9280.568,10446.66
Exp/Cntr=0.3,0.1

Type RM Length L Ch R = 1 ,3860.599,246.844800,246.844800,246.844800
XS GIS Cut Line= 6
758589.166130108764625.561271058759033.220567198764831.616605866
759125.742304507764862.055395594759295.172580135764888.887631911
759442.244021441764965.436036691759588.006307459765027.985983885
#Sta/Elev= 30
9153.4581245.2029222.3221238.5419259.4661236.8819362.6771229.246 9414.33 1227.18
9447.515 1227.619458.5761226.1839535.8011226.7059557.6351225.2089601.3041225.856
9626.5381224.2589698.0851224.5299749.9141219.9129780.4561209.5879800.7911204.485
9871.3191204.1549901.7091199.0949933.4151197.2679944.9681197.536 9956.55 1200.47
9968.1321201.5639979.7141196.57810002.78 1194.2110033.071202.94310070.07 1204.14
10092.081208.91510124.731213.15510157.371221.61710190.021226.92410236.821226.664
#Mann= 3 , 0 , 0
9153.458  0.0408       09153.458  0.0408       010236.82  0.0408       0
#XS Ineff= 2 , 0
       0                               0
Bank Sta=9153.458,10236.82
Exp/Cntr=0.3,0.1

Type RM Length L Ch R = 1 ,3613.755,246.844900,246.844900,246.844900
XS GIS Cut Line= 6
758581.336981856764653.782619408759030.475602857764900.982020735
759204.922490371765079.932908316759616.379680657765421.299918148
759975.991130119765669.115790213760464.490935308765972.210340611
#Sta/Elev= 30
9190.7171242.846 9438.761227.1449735.8891222.2719777.1151219.4439835.8941205.387
9926.782  1201.49954.5271193.9019994.5441190.97910018.591191.70910042.451203.313
 10058.41204.736 10123.91208.90710224.091209.01710254.881205.98310301.061193.889
10332.791194.12110361.011189.64910396.741189.86210446.041197.31910462.471200.888
10512.761218.66810529.921221.45510573.711219.79510876.731227.20510972.261225.302
11325.831232.688 11384.41236.04311467.921233.36611487.121234.03111500.961239.314
#Mann= 3 , 0 , 0
9190.717    0.04       09190.717    0.04       011500.96    0.04       0
#XS Ineff= 2 , 0
       0                10150.13       0
Bank Sta=9190.717,11500.96
Exp/Cntr=0.3,0.1

Type RM Length L Ch R = 1 , 3366.91,493.689600,493.689600,493.689600
XS GIS Cut Line= 6
758571.764820842764688.286920737758988.211485429764956.132925827
759040.603359809765061.251524926759062.720213153765266.288988134
 759304.46512495765578.953643876760060.157432558766179.769383546
#Sta/Elev= 30
9308.1281240.6669413.0351235.3119470.118 1229.949620.3391223.3369816.7941224.116
9875.1851221.7119907.7311210.106 9968.53 1202.639988.935 1191.999999.5091189.254
10010.081189.786 10030.41196.79910103.571198.50710125.331201.46310170.761202.986
 10217.71200.55710229.831197.85910241.971191.85110278.591189.12210316.371190.053
10354.49 1202.48 10367.61209.96110420.04 1216.1810740.151219.061 10766.91226.811
10832.421230.30211457.741230.90111469.971231.76711492.461240.27411500.741240.271
#Mann= 3 , 0 , 0
9308.128  0.0636       09308.128  0.0636       011500.74  0.0636       0
#XS Ineff= 2 , 0
       0                10169.81       0
Bank Sta=9308.128,11500.74
Exp/Cntr=0.3,0.1

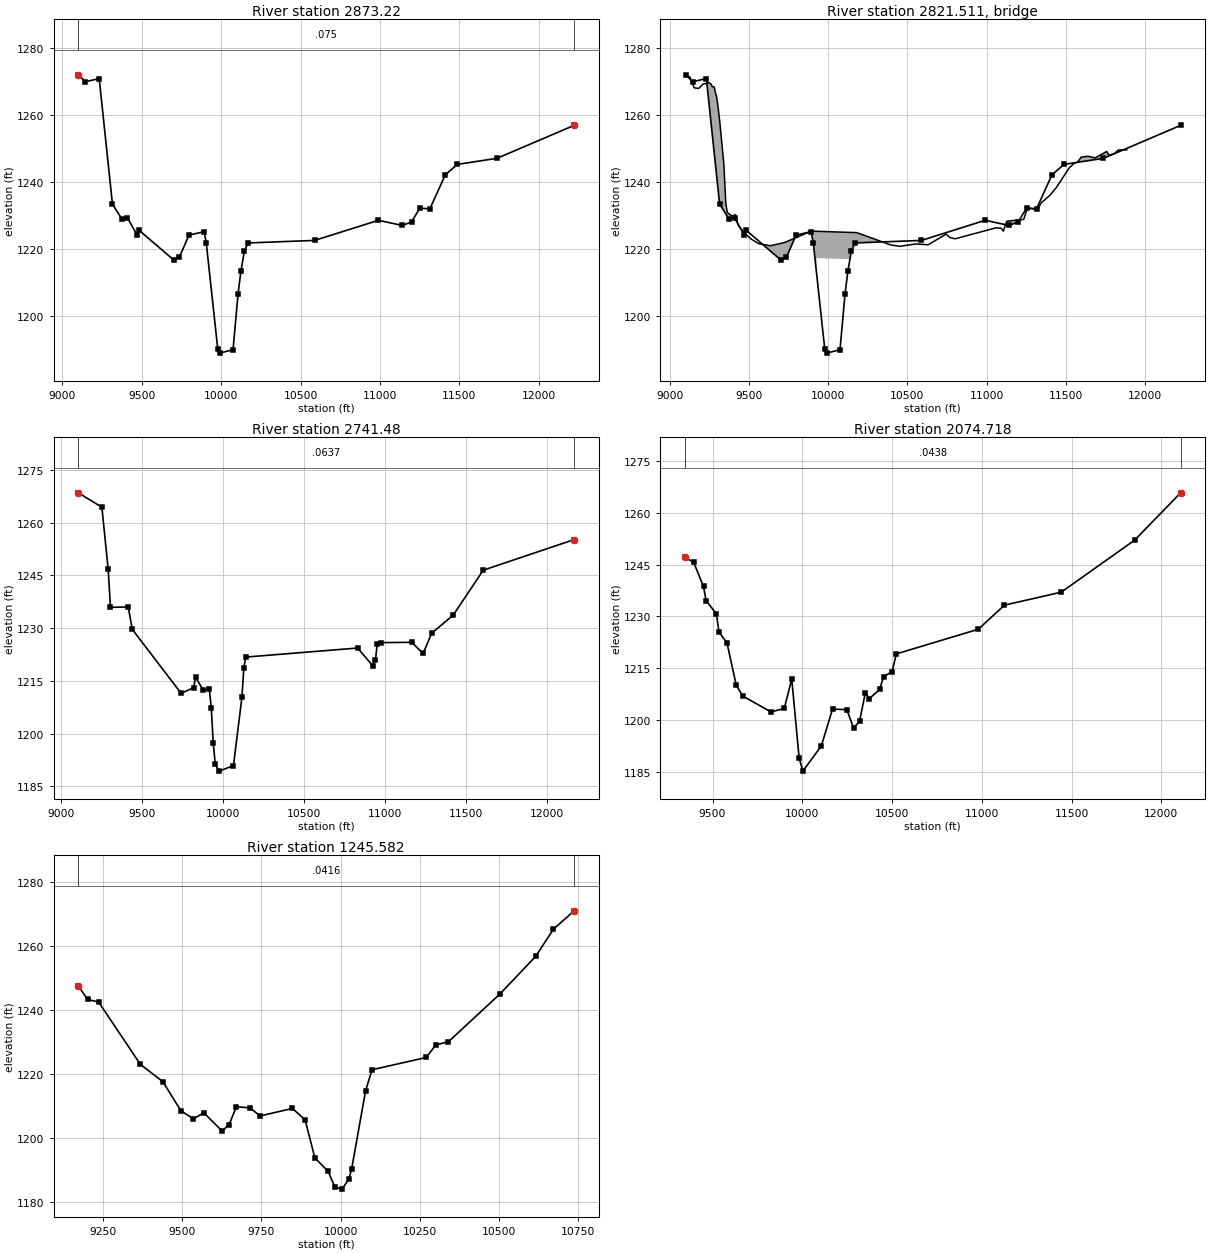
Type RM Length L Ch R = 1 , 2873.22,131.739900,131.739900,131.739900
XS GIS Cut Line= 6
758193.738524109764749.561223775758338.670556098764899.964628801
759013.670556009765929.131295428759255.337222666766187.464628816
760079.286633134 766529.83630161760385.689155161766844.127408877
#Sta/Elev= 30
9099.846 1272.099144.8991270.0289231.3681270.9779314.7911233.5529373.6611229.085
9409.4151229.3779471.624 1224.229483.6881225.6659700.841 1216.869737.0331217.726
9797.3541224.2549892.0871225.283 9905.931222.0249978.3151190.3619990.3791189.048
10074.831190.06710106.611206.77110124.491213.49910146.731219.62610170.251221.926
10588.821222.67810991.271228.68311142.15 1227.1411199.761228.20911251.881232.278
11315.42 1232.1311412.881242.27711488.681245.36411737.751247.17212224.641257.011
#Mann= 3 , 0 , 0
9099.846   0.075       09099.846   0.075       012224.64   0.075       0
#XS Ineff= 2 , 0
       09813.014        10221.03       0
Bank Sta=9099.846,12224.64
Exp/Cntr=0.3,0.1

Type RM Length L Ch R = 3 ,2821.511,,,
BEGIN DESCRIPTION:
END DESCRIPTION:
Bridge Culvert--1,0,-1,-1, 0
Deck Dist Width WeirC Skew NumUp NumDn MinLoCord MaxHiCord MaxSubmerge Is_Ogee
40.607550,50.524800,2.6,0, 60, 60, , , 0.95, 0, 0,0,,
 9095.19 9126.56 9154.60 9182.64 9210.68 9248.79 9263.06 9266.76 9280.78 9291.60
 9294.80 9304.65 9316.93 9341.48 9353.76 9363.20 9390.59 9415.14 9432.15 9464.25
 9513.36 9562.47 9636.14 9725.18 9893.96 9926.79 9926.7910132.1710132.1710181.00
10395.3310452.9510553.0410630.8610744.8710769.7710802.4911058.4411091.3911106.10
11124.3411130.2711234.1911251.1111267.1411322.0611344.0311398.9511442.8911519.78
11552.7311574.7011596.6711640.6111684.5511758.6511772.4211805.3711831.1511884.73
 1271.98 1271.50 1268.20 1268.04 1269.32 1269.74 1269.24 1268.63 1268.46 1266.12
 1265.91 1262.76 1257.67 1245.58 1233.92 1231.05 1229.98 1230.31 1227.19 1225.25
 1223.10 1221.69 1221.10 1222.06 1225.47 1225.41 1225.41 1225.08 1225.08 1225.00
 1221.33 1220.91 1221.63 1221.38 1224.56 1223.49 1223.17 1226.43 1226.33 1225.45
 1228.09 1228.45 1228.94 1231.41 1232.34 1231.90 1233.86 1236.11 1238.63 1244.21
 1245.70 1246.11 1247.52 1247.80 1247.31 1249.22 1248.10 1248.57 1249.65 1249.69
  271.98  271.50  268.20  268.04  269.32  269.74  269.24  268.63  268.46  266.12
  265.91  262.76  257.67  245.58  233.92  231.05  229.98  230.31  227.19  225.25
  223.10  221.69  221.10  222.06  225.47  225.41 1217.41 1217.08  225.08  225.00
  221.33  220.91  221.63  221.38  224.56  223.49  223.17  226.43  226.33  225.45
  228.09  228.45  228.94  231.41  232.34  231.90  233.86  236.11  238.63  244.21
  245.70  246.11  247.52  247.80  247.31  249.22  248.10  248.57  249.65  249.69
 9095.19 9126.56 9154.60 9182.64 9210.68 9248.79 9263.06 9266.76 9280.78 9291.60
 9294.80 9304.65 9316.93 9341.48 9353.76 9363.20 9390.59 9415.14 9432.15 9451.98
 9513.36 9562.47 9623.86 9725.18 9795.74 9909.12 9909.1210114.5010114.5010181.00
10395.3310452.9510553.0410630.8610744.8710769.7710802.4911058.4411091.3911106.10
11124.3411130.2711234.1911251.1111267.1411322.0611344.0311398.9511442.8911519.78
11552.7311574.7011596.6711640.6111684.5511758.6511772.4211805.3711831.1511884.73
 1271.98 1271.50 1268.20 1268.04 1269.32 1269.74 1269.24 1268.63 1268.46 1266.12
 1265.91 1262.76 1257.67 1245.58 1233.92 1231.05 1229.98 1230.31 1227.19 1225.94
 1223.10 1221.69 1221.10 1222.06 1223.71 1225.44 1225.44 1225.11 1225.11 1225.00
 1221.33 1220.91 1221.63 1221.38 1224.56 1223.49 1223.17 1226.43 1226.33 1225.45
 1228.09 1228.45 1228.94 1231.41 1232.34 1231.90 1233.86 1236.11 1238.63 1244.21
 1245.70 1246.11 1247.52 1247.80 1247.31 1249.22 1248.10 1248.57 1249.65 1249.69
  271.98  271.50  268.20  268.04  269.32  269.74  269.24  268.63  268.46  266.12
  265.91  262.76  257.67  245.58  233.92  231.05  229.98  230.31  227.19  225.94
  223.10  221.69  221.10  222.06  223.71  225.44 1217.44 1217.11  225.11  225.00
  221.33  220.91  221.63  221.38  224.56  223.49  223.17  226.43  226.33  225.45
  228.09  228.45  228.94  231.41  232.34  231.90  233.86  236.11  238.63  244.21
  245.70  246.11  247.52  247.80  247.31  249.22  248.10  248.57  249.65  249.69
BR Coef=-1 , 0 , 0 ,, 0 ,,,0.8,0,1,0,
WSPro=,,,, 1 ,,,, 0 ,,,, 0 ,,,,-1 ,-1 ,-1 , 0 , 0 , 0 , 0 , 0
BC Design=,, 0 ,, 0 ,,,,,,

Type RM Length L Ch R = 1 , 2741.48,666.762100,666.762100,666.762100
XS GIS Cut Line= 6
758099.294079632764838.450112656758584.503889352765483.297962114
758905.337222695765991.631295457759188.670556009766287.464628816
760057.293168068766670.568924919760255.341469258766892.150240555
#Sta/Elev= 30
9104.9311268.4919250.3931264.4019289.5821246.7329303.5791235.9129413.6931236.031
9438.1621229.6679740.535 1211.459817.442 1213.069829.6771215.9749878.6161212.318
9914.1681212.8169927.0761207.3119938.9011197.376 9951.641191.2619974.377 1189.32
10064.061190.87410116.281210.274 10128.11218.63710139.931221.76510831.931224.341
10923.981219.35510941.831220.89810952.761225.48210974.611225.87911165.681225.968
11236.92 1222.7911289.581228.55111422.721233.70411608.521246.48612170.521255.189
#Mann= 3 , 0 , 0
9104.931  0.0637       09104.931  0.0637       012170.52  0.0637       0
#XS Ineff= 2 , 0
       09812.674        10224.52       0
Bank Sta=9104.931,12170.52
Exp/Cntr=0.3,0.1

Type RM Length L Ch R = 1 ,2074.718,829.136200,829.136200,829.136200
XS GIS Cut Line= 6
757798.004349089765808.370990628758076.946339349766051.435801407
 758680.52763472766258.440474798758992.369334648766468.809446176
759335.739015291766855.737192934759795.668827603767575.323367943
#Sta/Elev= 30
9345.5551247.0649394.8461245.632 9449.751238.6669464.1241234.5979521.6161230.721
9536.1561225.4769580.5211222.385  9631.81210.2469667.3481207.0799825.524 1202.46
9899.567 1203.469941.2851211.9549982.3371189.22810002.831185.37910105.691192.599
10168.321203.28110248.08 1203.1110285.941197.796 10318.71199.74110351.471208.053
10373.89 1206.3210430.52 1208.9410453.171212.65110500.221214.09510523.791219.206
10980.51 1226.3211125.97 1233.2711442.451237.02211850.921252.01212107.461265.687
#Mann= 3 , 0 , 0
9345.555  0.0438       09345.555  0.0438       012107.46  0.0438       0
#XS Ineff= 2 , 0
       09860.534        10196.23       0
Bank Sta=9345.555,12107.46
Exp/Cntr=0.3,0.1

Type RM Length L Ch R = 1 ,1245.582,0.000000,0.000000,0.000000
XS GIS Cut Line= 6
 757670.33047299765950.451295367757897.942396671766311.727045655
757969.635567337766491.421814129757970.062551737766600.116331115
757895.124927193766915.515960813757982.797665954767412.143864781
#Sta/Elev= 30
 9172.911247.3839202.1291243.1529236.8351242.3599368.7641222.858 9439.661217.451
9496.5791208.3689535.6351205.8949568.8491207.7369626.1611202.0649648.6731204.049
 9671.131209.6589714.4591209.2759746.3511206.7599848.1091209.106 9888.241205.526
9918.8211193.6529960.7331189.4439982.3561184.448 10004.31183.88810025.971186.984
10035.031190.28710078.711214.58310099.271221.20210270.011225.02710300.061228.929
 10340.21229.962 10502.11244.82810614.931256.58610671.331265.12810736.611270.858
#Mann= 3 , 0 , 0
 9172.91  0.0416       0 9172.91  0.0416       010736.61  0.0416       0
#XS Ineff= 2 , 0
       09775.366        10095.93       0
Bank Sta=9172.91,10736.61
Exp/Cntr=0.3,0.1